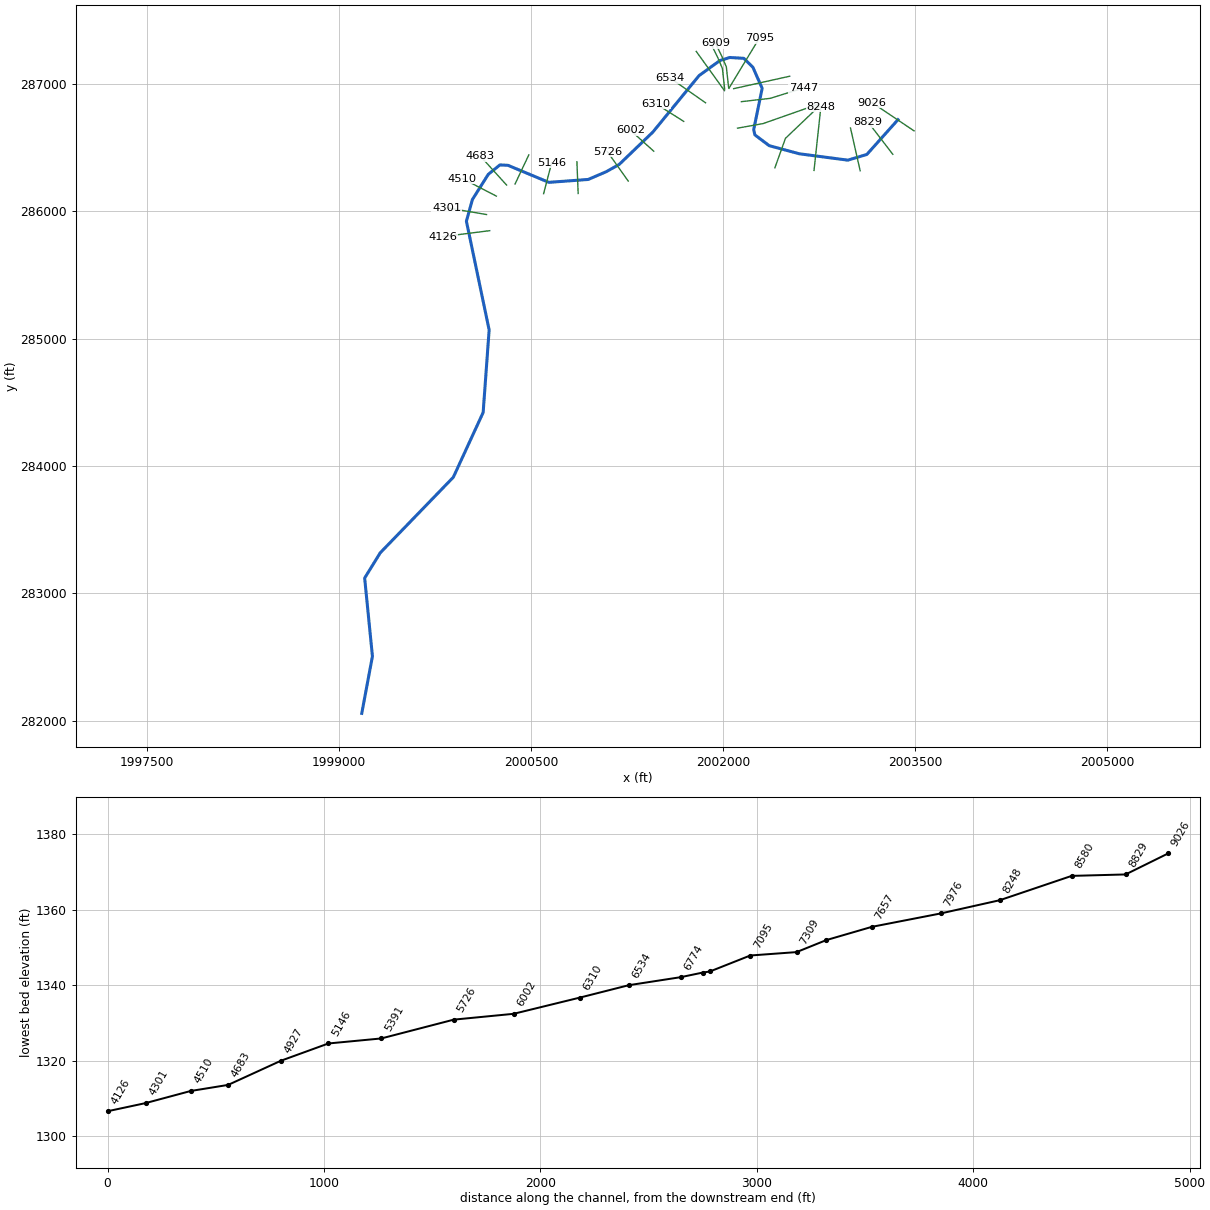
--- LICKCK2_AE.prj (project) ---

Proj Title=LICKCK2_AE
Current Plan=p01
Default Exp/Contr=0,0
English Units
Geom File=g01
Flow File=f01
Plan File=p01
BEGIN DESCRIPTION:
Stream Name: Lick Creek
Flood Zone:  Detailed
Summers County, West Virginia
HEC-RAS Version: 5.0.7
Hydrology Method: Regression
Model Notes:
END DESCRIPTION:
DSS Export Rating Curves= 0
DSS Export Rating Curve Sorted= 0
DSS Export Volume Flow Curves= 0
DXF OffsetX= 0
DXF OffsetY= 0
DXF ScaleX= 0
DXF ScaleY= 0

--- LICKCK2_AE.p01 (plan) ---

Plan Title=Floodplain
Program Version=5.07
Short Identifier=Floodplain
Geom File=g01
Flow File=f01
Subcritical Flow
K Sum by GR= 0
Std Step Tol= 0.01
Critical Tol= 0.01
Num of Std Step Trials= 20
Max Error Tol= 0.3
Flow Tol Ratio= 0.001
Split Flow NTrial= 30
Split Flow Tol= 0.02
Split Flow Ratio= 0.02
Log Output Level= 0
Friction Slope Method= 1
Unsteady Friction Slope Method= 2
Unsteady Bridges Friction Slope Method= 1
Parabolic Critical Depth
Global Vel Dist= 0 , 0 , 0
Global Log Level= 0
CheckData=True
Encroach Param=-1 ,10,10, 2
Encroach River=LICKCK2_AE
Encroach Reach=Main
Encroach Node=9026
       1   115.2   202.2
Encroach Node=8829
       1     104     198
Encroach Node=8580
       1    71.8   159.9
Encroach Node=8248
       1      84   157.5
Encroach Node=7976
       1     118     194
Encroach Node=7657
       1   104.3     185
Encroach Node=7447
       1      88     192
Encroach Node=7309
       1     150     240
Encroach Node=7095
       1     185     295
Encroach Node=6909
       1     178     245
Encroach Node=6876
       1   176.4  244.33
Encroach Node=6774
       1   171.5     234
Encroach Node=6534
       1     137   202.2
Encroach Node=6310
       1      99   158.8
Encroach Node=6002
       1      70   143.6
Encroach Node=5726
       1   120.7     201
Encroach Node=5391
       1    59.5   134.1
Encroach Node=5146
       1      73     125
Encroach Node=4927
       1    91.3     163
Encroach Node=4683
       1   125.9   188.8
Encroach Node=4510
       1   110.8   182.5
Encroach Node=4301
       1   109.5   166.1
Encroach Node=4126
       1   143.7   201.4
Encroach Node=3919
       1   118.7     175
Encroach Node=3757
       1   157.5   228.6
Encroach Node=3588
       1   229.6  323.36
Encroach Node=3318
       1     221   324.6
Encroach Node=3082
       1   160.7   249.7
Encroach Node=2891
       1     138     203
Encroach Node=2686
       1   105.7     170
Encroach Node=2401
       1   145.8   235.4
Encroach Node=2074
       1     150     238
Encroach Node=1785
       1   245.3   308.7
Encroach Node=1662
       1   237.9     320
Encroach Node=1626
       1     219     330
Encroach Node=1512
       1     219  321.86
Encroach Node=1157
       1   386.1   458.4
Encroach Node=592
       1   463.9   579.3
Mapping Interval=1HOUR
Computation Time Step Use Courant=        0
Computation Time Step Use Time Series=    0
Computation Time Step Count To Double=0
Computation Time Step Max Doubling=0
Computation Time Step Max Halving=0
Computation Time Step Residence Courant=0
Run HTab= 0
Run UNet= 0
Run Sediment= 0
Run PostProcess= 0
Run WQNet= 0
Run RASMapper= 0
UNET Theta= 0
UNET Theta Warmup= 0
UNET ZTol= 0
UNET ZSATol= 0
UNET MxIter= 0
UNET Max Iter WO Improvement= 0
UNET MaxInSteps= 0
UNET DtIC= 0
UNET DtMin= 0
UNET MaxCRTS= 0
UNET WFStab= 0
UNET SFStab= 0
UNET WFX= 1
UNET SFX= 1
UNET 1D Methodology=Finite Difference
UNET DSS MLevel= 1
UNET Pardiso=0
UNET DZMax Abort= 0
UNET Use Existing IB Tables= 0
UNET Froude Reduction=False
UNET Froude Limit= 0
UNET Froude Power= 0
UNET D1 Cores= 0
UNET D2 Coriolis=0
UNET D2 Cores= 0
UNET D2 Theta= 1
UNET D2 Theta Warmup= 1
UNET D2 Z Tol= 0.01
UNET D2 Volume Tol= 0.01
UNET D2 Max Iterations= 20
UNET D2 Equation= 0
UNET D2 RampUpFraction=0.1
UNET D2 TimeSlices= 1
UNET D2 BCVolumeCheck=0
UNET D1D2 MaxIter= 0
UNET D1D2 ZTol=0.01
UNET D1D2 QTol=0.1
UNET D1D2 MinQTol=1
Write IC File= 0
Write IC File at Fixed DateTime=0
Write IC File at Sim End=0
Echo Input=False
Echo Parameters=False
Echo Output=False
Write Detailed= 0
HDF Write Warmup=0
HDF Write Time Slices=0
HDF Flush=0
HDF Face Node Velocities=0
HDF Compression= 1
HDF Chunk Size= 1
HDF Spatial Parts= 1
HDF Use Max Rows=0
HDF Fixed Rows= 1
Calibration Method= 0
Calibration Iterations= 20
Calibration Max Change=0.05
Calibration Tolerance=0.2
Calibration Maximum=1.5
Calibration Minimum=0.5
Calibration Optimization Method= 1
WQ AD Non Conservative
WQ ULTIMATE=-1
WQ Max Comp Step=1HOUR
WQ Output Interval=15MIN
WQ Output Selected Increments= 0
WQ Output face flow=0
WQ Output face velocity=0
WQ Output face area=0
WQ Output face dispersion=0
WQ Output cell volume=0
WQ Output cell surface area=0
WQ Output cell continuity=0
WQ Output cumulative cell continuity=0
WQ Output face conc=0
WQ Output face dconc_dx=0
WQ Output face courant=0
WQ Output face peclet=0
WQ Output face adv mass=0
WQ Output face disp mass=0
WQ Output cell mass=0
WQ Output cell source sink temp=0
WQ Output nsm pathways=0
WQ Output nsm derived pathways=0
WQ Output MaxMinRange=-1
WQ Daily Max Min Mean=-1
WQ Daily Range=0
WQ Daily Time=0
WQ Create Restart=0
WQ Fixed Restart=0
WQ System Summary=0
WQ Write To DSS=0
WQ Use Fixed Temperature=0
Sorting and Armoring Iterations= 10
XS Update Threshold= 0.02
Bed Roughness Predictor= 0
Hydraulics Update Threshold= 0.02
Energy Slope Method= 1
Volume Change Method= 1
Sediment Retention Method= 0
XS Weighting Method= 0
Number of US Weighted Cross Sections= 1
Number of DS Weighted Cross Sections= 1
Upstream XS Weight=0
Main XS Weight=1
Downstream XS Weight=0
Number of DS XS's Weighted with US Boundary= 1
Upstream Boundary Weight= 1
Weight of XSs Associated with US Boundary= 0
Number of US XS's Weighted with DS Boundary= 1
Downstream Boundary Weight= 0.5
Weight of XSs Associated with DS Boundary= 0.5
Percentile Method= 0
Sediment Output Level= 3
Mass or Volume Output= 0
Output Increment Type= 1
Profile and TS Output Increment= 1
XS Output Flag= 0
XS Output Increment= 10
Write Gradation File= 0
Read Gradation Hotstart= 0
Write HDF5 File= 1
Write Binary Output= 1
Write DSS Sediment File= 0
SV Curve= 0
Specific Gage Flag= 0

--- LICKCK2_AE.f01 (steady flow) ---

Flow Title=Flows
Program Version=5.07
Number of Profiles= 7
Profile Names=01pct,FW,10pct,04pct,02pct,0_2pct,01plus
River Rch & RM=LICKCK2_AE,Main            ,9026
    5598    5598    3231    4117    4835    7492    8279
Boundary for River Rch & Prof#=LICKCK2_AE,Main            , 1
Up Type= 0
Dn Type= 3
Dn Slope=0.007277
Boundary for River Rch & Prof#=LICKCK2_AE,Main            , 2
Up Type= 0
Dn Type= 3
Dn Slope=0.007277
Boundary for River Rch & Prof#=LICKCK2_AE,Main            , 3
Up Type= 0
Dn Type= 3
Dn Slope=0.007277
Boundary for River Rch & Prof#=LICKCK2_AE,Main            , 4
Up Type= 0
Dn Type= 3
Dn Slope=0.007277
Boundary for River Rch & Prof#=LICKCK2_AE,Main            , 5
Up Type= 0
Dn Type= 3
Dn Slope=0.007277
Boundary for River Rch & Prof#=LICKCK2_AE,Main            , 6
Up Type= 0
Dn Type= 3
Dn Slope=0.007277
DSS Import GetInterval= 0
DSS Import GetPeak= 0
DSS Import FillOption= 0

--- LICKCK2_AE.g01 (geometry) ---

Geom Title=Geometry
Program Version=5.07

River Reach=LICKCK2_AE      ,Main
Reach XY= 30
     2003364.992      286717.822     2003121.925      286444.993
     2002972.967      286400.201     2002594.321      286450.201
     2002359.425      286513.743     2002246.926      286598.638
     2002238.071      286639.784     2002304.125       286964.18
     2002231.821      287128.717     2002161.019      287199.184
     2002051.594      287205.748     2001974.661      287182.104
     2001811.695      287064.215     2001450.571      286620.904
     2001186.514      286365.979     2001085.988      286309.489
     2000944.929      286248.725     2000637.854      286225.939
     2000318.844      286359.402     2000255.703      286362.845
     2000164.618      286288.998     2000040.444      286091.137
     1999993.712      285920.732     2000171.275       285068.17
  2000124.458641284420.0758718471999891.52546145283912.048487268
     1999320.363      283318.604     1999198.835      283120.687
     1999259.599      282506.972     1999176.203      282058.903

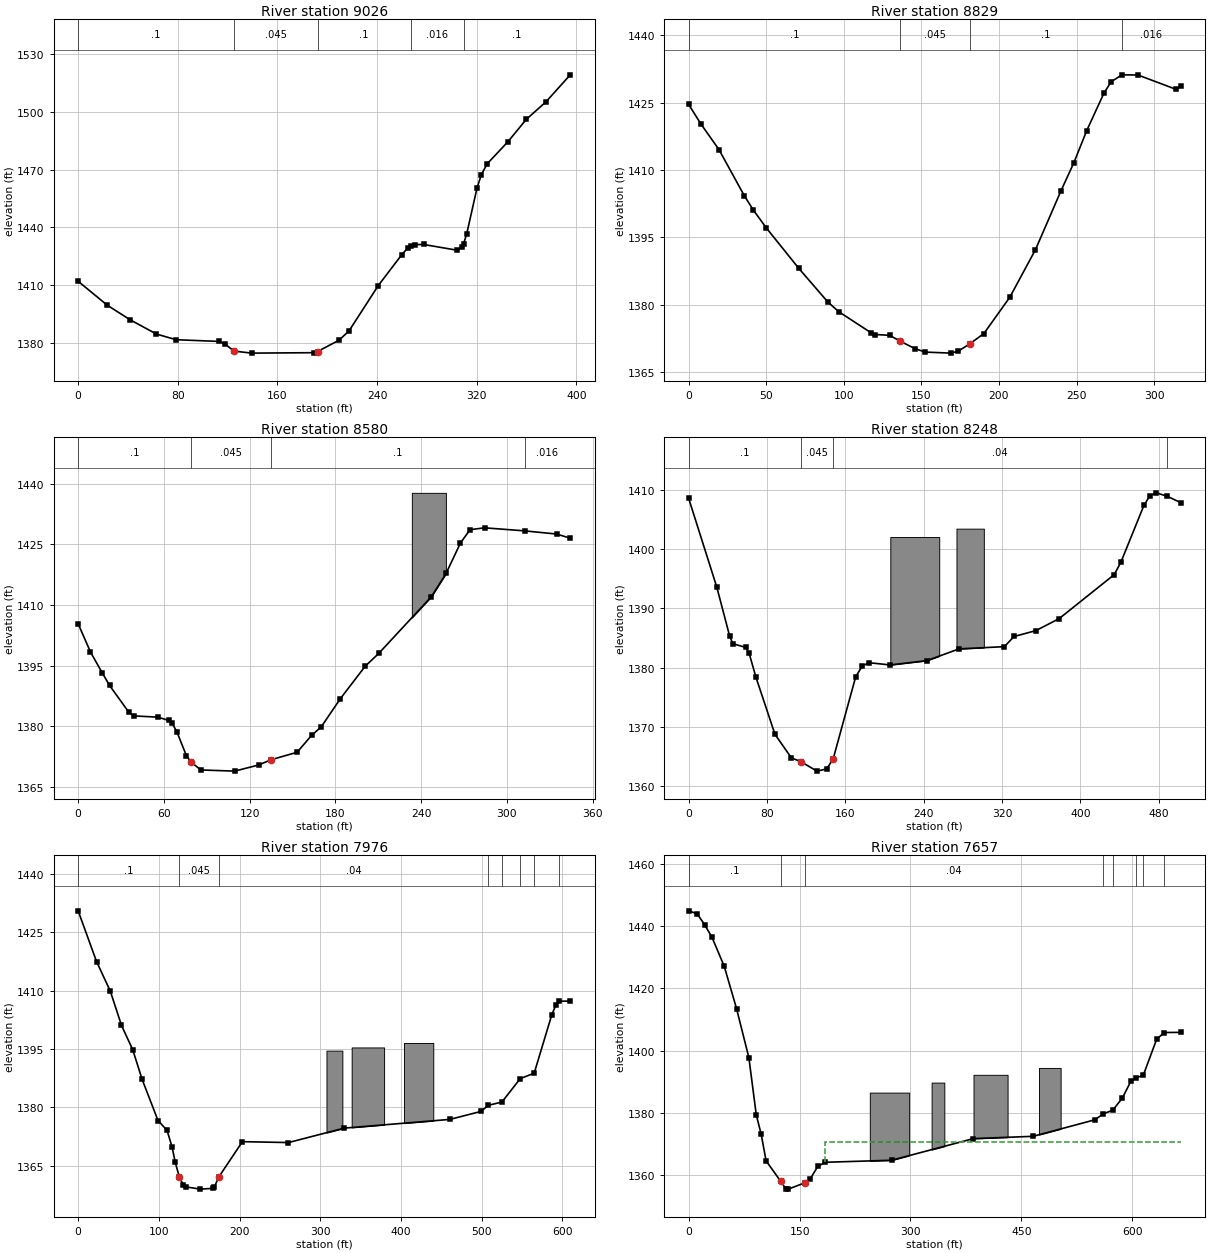
Type RM Length L Ch R = 1 ,9026    ,214.7,197,186.5
Node Name=C
XS GIS Cut Line= 3
2003490.66191648286629.9481163362003436.85954918286666.195515757
2003163.15318263286850.940258856
#Sta/Elev= 30
       0 1412.11    23.3 1399.74    41.6 1392.19    62.9 1384.73    78.7 1381.81
   113.4 1380.92   117.9 1379.55   125.2 1375.91   139.4 1374.86     189 1375.09
   192.2  1375.7   209.3 1381.51   217.4  1386.3     241 1409.91   259.9 1425.95
   264.6 1429.32     267 1430.31   270.4 1431.12   277.4 1431.17   304.3 1428.19
   308.3 1429.78   309.5 1431.65   311.9 1436.49   320.2 1460.37   323.7 1467.36
   328.4    1473     345 1484.39   359.7 1495.96   375.6 1505.12   395.1 1519.11
#Mann= 5 ,-1 , 0
       0      .1       0   125.2    .045       0   192.2      .1       0
     267    .016       0   309.5      .1       0
Bank Sta=125.2,192.2
XS Rating Curve= 0 ,0
Exp/Cntr(USF)=0,0
Exp/Cntr=0.3,0.1

Type RM Length L Ch R = 1 ,8829    ,257.7,249,224.8
XS GIS Cut Line= 2
2003324.46670206286446.1769387222003131.74134641286698.096510752
#Sta/Elev= 30
       0 1424.58     7.8 1420.28    19.5 1414.56    35.9 1404.26    41.7 1401.09
    49.9 1397.19      71 1388.12    89.7 1380.66    96.7 1378.51   117.8 1373.76
   120.2 1373.43   129.5 1373.25   136.3 1371.95   145.9 1370.28   152.5 1369.52
   169.3 1369.29   173.9 1369.77     181 1371.31   190.3 1373.65     207 1381.73
   223.5 1392.28     240 1405.41   248.3 1411.65   256.5 1418.72   267.6 1427.07
   272.3 1429.63   279.3 1431.17   289.6 1431.13   314.4 1427.91   317.2 1428.61
#Mann= 4 ,-1 , 0
       0      .1       0   136.3    .045       0     181      .1       0
   279.3    .016       0
Bank Sta=136.3,181
XS Rating Curve= 0 ,0
Exp/Cntr(USF)=0,0
Exp/Cntr=0.3,0.1

Type RM Length L Ch R = 1 ,8580    ,337.2,332.2,313.5
XS GIS Cut Line= 2
2003069.79391066286316.7756284982002994.08037808286652.668391206
#Sta/Elev= 30
       0 1405.34     8.6 1398.37    16.9 1393.17      22 1390.08    35.5 1383.45
    38.8 1382.56    55.6 1382.26    63.6 1381.43    65.7  1380.8    69.1 1378.61
    75.8 1372.68    79.2 1371.06    85.9  1369.2   109.5 1368.91   126.3 1370.43
   134.9 1371.72   153.2 1373.57   163.3 1377.75     170 1379.82   183.4 1386.79
   200.8 1394.83   210.3    1398   247.2 1412.07   257.4 1417.77   267.5 1425.32
   274.2 1428.59   284.3 1429.05   312.3  1428.3   334.8 1427.51   344.3 1426.48
#Mann= 4 ,-1 , 0
       0      .1       0    79.2    .045       0   134.9      .1       0
   312.3    .016       0
#Block Obstruct= 1 ,-1
  233.46  257.29  1437.7
Bank Sta=79.2,134.9
XS Rating Curve= 0 ,0
Exp/Cntr(USF)=0,0
Exp/Cntr=0.3,0.1

Type RM Length L Ch R = 1 ,8248    ,278.3,272.4,264.6
XS GIS Cut Line= 2
2002709.12217365286319.528847865 2002762.8099513286819.238162876
#Sta/Elev= 30
       0 1408.61    28.7 1393.61    41.9 1385.28    45.2 1384.02    58.4  1383.4
    61.7 1382.44    68.6  1378.4    88.1  1368.7   104.9 1364.71   114.5 1364.08
     131 1362.47   140.9 1362.84   147.5 1364.51   170.6 1378.45   177.2 1380.23
   183.8 1380.82   205.7 1380.44   243.2 1381.17   276.2 1383.16   322.4 1383.53
   332.3 1385.25   354.7 1386.25   378.4 1388.28   434.6 1395.72   441.4 1397.82
   464.9 1407.42   470.9 1409.04   477.5 1409.56   488.7 1408.98   502.6 1407.89
#Mann= 4 ,-1 , 0
       0      .1       0   114.5    .045       0   147.5     .04       0
   488.7    .016       0
#Block Obstruct= 2 ,-1
  205.92  255.87 1402.08  273.48  301.44  1403.5
Bank Sta=114.5,147.5
XS Rating Curve= 0 ,0
Exp/Cntr(USF)=0,0
Exp/Cntr=0.3,0.1

Type RM Length L Ch R = 1 ,7976    ,342.1,318.4,280.5
XS GIS Cut Line= 3
2002403.51482398286340.1779931132002486.11140497286571.448419895
2002749.04385447286823.367991926
#Sta/Elev= 30
       0  1430.5    22.8 1417.46    39.8 1409.88    53.7 1401.05    67.6 1394.82
    79.3 1387.15      99 1376.57   110.1 1374.11   116.4 1369.77   120.3 1365.88
   125.5 1361.97   130.3 1360.09   133.8 1359.54   151.2 1358.97   166.6 1359.16
   168.7  1359.5   174.3 1362.11   203.5 1371.17   260.6 1370.94   329.6 1374.65
   460.5 1376.89     499 1378.94   508.3 1380.52     525 1381.35   547.7 1387.37
     565 1388.77   586.6 1403.65   591.8 1406.29   596.1 1407.27   609.7  1407.3
#Mann= 8 ,-1 , 0
       0      .1       0   125.5    .045       0   174.3     .04       0
   508.3    .016       0     525     .05       0   547.7    .016       0
     565     .05       0   596.1    .016       0
#Block Obstruct= 3 ,-1
  307.66  327.37 1394.57  338.87  379.04 1395.39  403.71  439.97 1396.53
Bank Sta=125.5,174.3
XS Rating Curve= 0 ,0
Exp/Cntr(USF)=0,0
Exp/Cntr=0.3,0.1

Type RM Length L Ch R = 1 ,7657    ,198.4,210.6,202.3
XS GIS Cut Line= 3
2002111.67357113286651.291781523 2002311.2819752286687.083633287
2002747.66724479286841.263917808
#Sta/Elev= 30
       0 1444.95    11.4 1444.01    21.4 1440.54    31.4 1436.51    48.1 1427.09
    64.7 1413.52    81.4 1397.71    91.4 1379.33    98.1 1373.02   104.7 1364.51
   124.4 1357.96   131.4 1355.53   134.7 1355.42   157.7 1357.51   164.7 1358.83
   174.7 1362.77   184.7 1364.06   274.4 1364.71   385.2 1371.68   465.8 1372.41
   549.3 1377.72   560.8 1379.64   573.6 1380.82   586.6 1384.74     598 1390.11
   604.6  1391.2   614.8 1392.02   632.8 1403.56   643.1  1405.8   665.6 1405.85
#Mann= 8 ,-1 , 0
       0      .1       0   124.4    .045       0   157.7     .04       0
   560.8    .016       0   573.6     .05       0   604.6    .016       0
   614.8     .05       0   643.1    .016       0
#XS Ineff= 2 , 0
       0                     185       0 1370.45
Permanent Ineff=
       F       F
#Block Obstruct= 4 ,-1
  244.95  298.21 1386.47  328.54  345.77 1389.69  385.21   431.3  1392.2
  473.74  503.06 1394.41
Bank Sta=124.4,157.7
XS Rating Curve= 0 ,0
Exp/Cntr(USF)=0,0
Exp/Cntr=0.3,0.1

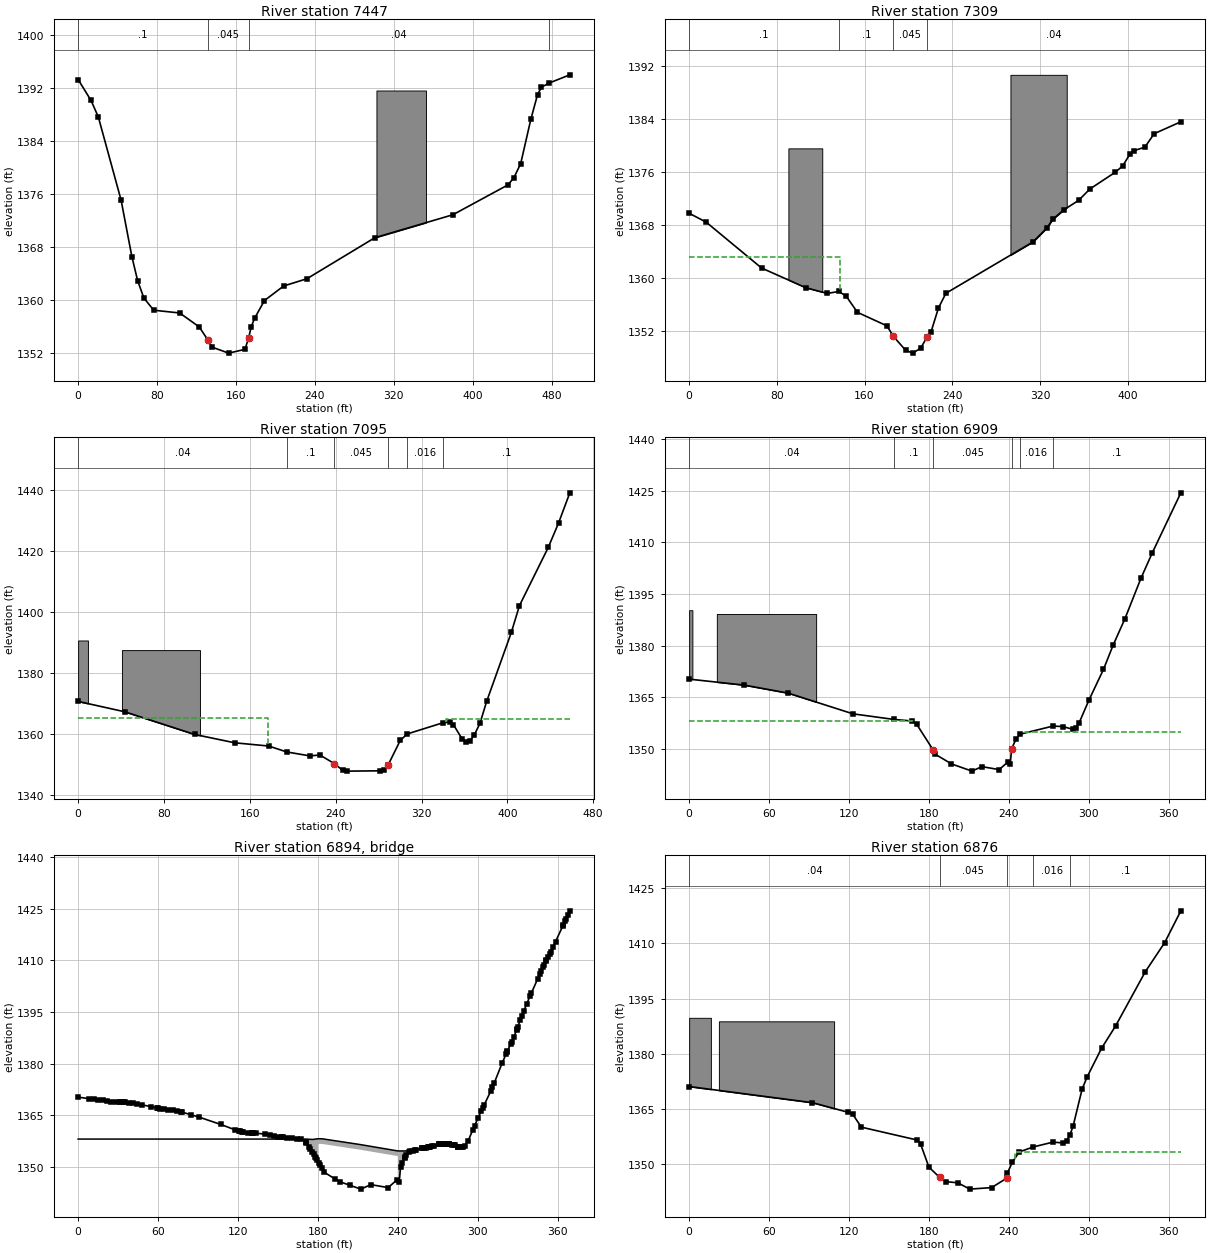
Type RM Length L Ch R = 1 ,7447    ,125.1,137.5,136.2
XS GIS Cut Line= 3
2002141.95898416 286859.159843692002367.72297221286885.315427671
2002626.52559266286966.535398982
#Sta/Elev= 30
       0 1393.28    13.1 1390.11    20.5 1387.61    43.6 1375.02    54.5 1366.49
    60.4 1362.83    66.7 1360.24    76.6  1358.4     103 1357.98   122.8 1355.87
   131.5 1353.91   136.1  1352.8   152.6 1351.91   169.1 1352.48   172.9 1354.19
   175.4 1355.86     179  1357.2   188.9 1359.86   208.4 1362.06     232 1363.16
   300.8 1369.36   379.9 1372.83   435.7 1377.34   441.8 1378.43   448.7 1380.56
     459 1387.27   465.8    1391   469.7 1392.11   477.6 1392.75   498.5 1393.99
#Mann= 4 ,-1 , 0
       0      .1       0   131.5    .045       0   172.9     .04       0
   477.6    .016       0
#Block Obstruct= 1 ,-1
  302.46  352.64 1391.62
Bank Sta=131.5,172.9
XS Rating Curve= 0 ,0
Exp/Cntr(USF)=0,0
Exp/Cntr=0.3,0.1

Type RM Length L Ch R = 1 ,7309    ,176.8,213.9,242
XS GIS Cut Line= 2
 2002081.3881581286961.0289602492002519.15003737287058.768247758
#Sta/Elev= 30
       0 1369.81    15.6 1368.46    66.1 1361.55   106.4 1358.59   125.9 1357.73
   136.7 1358.02   143.4 1357.28   153.5 1354.88   180.4 1352.84   186.4 1351.24
   197.4 1349.17   203.9 1348.73   211.1 1349.46   217.3 1351.22   220.7 1351.96
   227.4 1355.53   234.2 1357.75   313.7  1365.5   326.6 1367.64   331.6 1368.89
   341.7 1370.32   355.2 1371.74   365.6 1373.47   388.8    1376   395.5 1376.95
   402.2 1378.75   405.6 1379.23   415.7 1379.77   424.2  1381.8   448.5 1383.59
#Mann= 4 ,-1 , 0
       0      .1       0   136.7      .1       0   186.4    .045       0
   217.3     .04       0
#XS Ineff= 2 , 0
          137.18 1363.22
Permanent Ineff=
       F       F
#Block Obstruct= 2 ,-1
   90.52  121.42 1379.59  293.07  344.41 1390.67
Bank Sta=186.4,217.3
XS Rating Curve= 0 ,0
Exp/Cntr(USF)=0,0
Exp/Cntr=0.3,0.1

Type RM Length L Ch R = 1 ,7095    ,144.8,186.5,208.5
XS GIS Cut Line= 2
2002044.21969666286963.7821796152002280.99656217287356.115939335
#Sta/Elev= 30
       0 1370.71    43.4 1367.31   108.6 1359.87   145.9 1357.13   177.7 1356.06
   194.3 1354.13   215.8 1352.84   225.4 1353.11   238.9 1350.27   246.5 1348.12
   250.4 1347.83     281 1347.93   285.2 1348.29   288.7  1349.7   300.2 1357.92
   306.7 1360.03   340.1 1363.72   346.2 1363.92   349.7 1363.13   357.7 1358.45
   361.6  1357.5   365.3 1357.86   369.2  1359.7   374.5 1363.53   380.7 1370.71
   403.7 1393.36   411.3 1402.17   438.1 1421.24   447.7 1429.24   458.2 1439.17
#Mann= 6 ,-1 , 0
       0     .04       0   194.3      .1       0   238.9    .045       0
   288.7      .1       0   306.7    .016       0   340.1      .1       0
#XS Ineff= 2 , 0
          177.18 1365.38   343.1         1364.87
Permanent Ineff=
       F       F
#Block Obstruct= 2 ,-1
       0    9.14 1390.71   40.82  113.53 1387.55
Bank Sta=238.9,288.7
XS Rating Curve= 0 ,0
Exp/Cntr(USF)=0,0
Exp/Cntr=0.5,0.3

Type RM Length L Ch R = 1 ,6909    ,33.2,33.3,33.2
BEGIN DESCRIPTION:
Channel burn from 54089LIC042BU
END DESCRIPTION:
XS GIS Cut Line= 4
2002042.10389522286969.6230005642002024.30658248287131.780683868
2001986.99345956 287219.305537052001938.51339533  287318.9388838
#Sta/Elev= 30
       0 1370.29    41.4 1368.56    74.4 1366.23     123 1360.22   153.7  1358.6
   167.2 1358.15   170.7 1357.26   183.3 1349.66  184.62 1348.53  196.94 1345.69
  212.31  1343.6   219.7 1344.91  232.71 1344.04  239.01 1346.16  241.04 1345.68
   242.1 1350.14   245.6 1353.06   248.3 1354.31   273.1 1356.67   280.4 1356.54
   287.8 1355.76   290.2 1356.24   292.7 1357.56   300.1 1364.19     311 1373.09
   318.3 1380.17   327.1 1387.79   339.3 1399.69   347.5  1406.8   369.1 1424.35
#Mann= 6 ,-1 , 0
       0     .04       0   153.7      .1       0   183.3    .045       0
   242.1      .1       0   248.3    .016       0   273.1      .1       0
#XS Ineff= 2 , 0
             168 1358.13     252         1354.85
Permanent Ineff=
       F       F
#Block Obstruct= 2 ,-1
       0    2.43 1390.29   20.78   95.33  1389.2
Bank Sta=183.3,242.1
XS Rating Curve= 0 ,0
Exp/Cntr(USF)=0,0
Exp/Cntr=0.5,0.3

Type RM Length L Ch R = 3 ,6894    ,,,
BEGIN DESCRIPTION:
Unnamed Road
Bridge Survey ID: 54089LIC040
Assumed no railing because railing would not obstruc 50% or more of flow.
END DESCRIPTION:
Bridge Culvert--1,0,-1,-1, 0
Deck Dist Width WeirC Skew NumUp NumDn MinLoCord MaxHiCord MaxSubmerge Is_Ogee
12,12,2.6,0, 10, 10, , , 0.98, 0, 0,0,,
       0     171     176     180     183     212     240     243     252     256
1358.1251358.125 1358.011358.2171358.2171356.518 1354.68 1354.681354.6621355.233
                        1356.7171356.7171355.018 1353.18
       0     171     176     180     183     212     240     243     252     256
1358.1251358.125 1358.011358.2171358.2171356.518 1354.68 1354.681354.662    1354
                        1356.7171356.7171355.018 1353.18
BR Coef=-1 , 1 , 0 ,, 0 ,,,0.8,0,1.2,0,
WSPro=,,,, 1 ,,,, 0 ,,,, 0 ,,,,-1 ,-1 ,-1 , 0 , 0 , 0 , 0 , 0
BR U #Sta/Elev= 153
       0 1370.29     8.1 1369.85    11.7 1369.69      15 1369.51    18.3 1369.37
    21.6 1369.15    24.9 1368.97    28.2 1368.93    31.5 1368.93    32.5 1368.91
    34.1 1368.85    35.5 1368.82    38.4 1368.71    41.4 1368.56    44.4 1368.33
      48 1368.07    54.6 1367.54    59.3 1367.08      60 1367.02    61.2  1366.9
    64.5 1366.71    67.8 1366.61    71.1 1366.47    74.4 1366.23    77.1    1366
    77.8 1365.95    84.4 1365.23      91 1364.47   106.9 1362.39   117.4 1360.87
   120.7 1360.46   121.7 1360.36     123 1360.22     124 1360.13   127.3    1360
   130.5 1359.94   130.6 1359.94   131.4 1359.91   133.9 1359.84   140.5 1359.52
   143.8  1359.3   147.1 1358.98   150.4 1358.75   152.7 1358.64   153.7  1358.6
     157 1358.48   160.3 1358.38   164.3 1358.22   167.2 1358.15   170.7 1357.26
     171 1357.07   173.3 1355.82   174.3  1355.3   175.8 1354.37   176.7 1353.71
   177.9 1352.92   178.3 1352.67   179.4 1351.96   180.8 1351.16   181.4 1350.69
   183.3 1349.66  184.62 1348.53  192.88 1346.54  196.94 1345.69  203.95 1344.72
  212.31  1343.6   219.7 1344.91  232.71 1344.04  239.01 1346.16  241.04 1345.68
   242.1 1350.14   243.3 1351.14   245.1 1352.63   245.6 1353.06   246.3 1353.43
   248.3 1354.31   249.2 1354.62   251.3 1354.79   252.8 1354.91   253.3 1354.95
   258.3  1355.4   258.3 1355.41   259.9 1355.55   260.8 1355.62   262.6 1355.77
   263.3 1355.82   263.6 1355.86   264.5 1355.95   265.7 1356.06   267.2 1356.21
   270.6 1356.57   270.9 1356.59   271.6 1356.62   273.1 1356.67   274.5 1356.71
   275.5  1356.7   277.6 1356.69     278 1356.68   278.2 1356.67   278.7 1356.64
   280.4 1356.54   281.8 1356.42   282.9 1356.28   285.1 1355.92   285.3 1355.88
   285.5 1355.86   287.8 1355.76   289.1 1355.84   290.2 1356.24   292.7 1357.56
   296.4 1360.87   297.6 1361.97   300.1 1364.19   302.5 1366.18   303.7 1367.15
     305 1368.15   309.9 1372.13     311 1373.09   312.3 1374.33   318.3 1380.17
   321.4 1382.93     322 1383.45   322.2 1383.62   324.6  1385.6   325.6 1386.43
   327.1 1387.79   329.3 1389.91   329.5 1390.19   330.1 1390.77     332 1392.76
   332.9  1393.7   334.4 1395.16   336.6  1397.2   339.3 1399.69   340.2 1400.45
   345.1  1404.7   346.7 1406.11   347.5  1406.8   349.2  1408.1   349.8 1408.64
   351.1 1409.72   351.6 1410.07   352.6 1410.83   354.1 1411.96   354.8 1412.52
   356.5 1413.87   358.4 1415.42   363.9 1420.01     364 1420.13   365.7 1421.54
   366.3 1422.03   367.6 1423.05   369.1 1424.35
BR U #Mann= 6
       0     .04   153.7      .1   183.3     .04   242.1      .1   248.3    .016
   273.1      .1
BR D #Sta/Elev= 163
       0 1371.14     3.9 1370.86     7.2 1370.66    13.8 1370.42    18.2 1370.18
    26.8 1369.82    30.1 1369.61    33.6 1369.43      36  1369.4    43.5 1369.25
    46.8 1369.11    53.4 1368.77    56.8 1368.61    62.8 1368.29    67.6 1367.99
    76.5 1367.53    86.4 1367.09    89.5 1366.92    92.5 1366.77    95.5 1366.56
    99.6 1366.22   102.9 1366.05   106.2  1365.8   112.8 1365.01   116.1 1364.56
   119.4 1364.15   122.3 1363.75   122.7 1363.66   123.2 1363.37   125.2  1362.3
     126 1361.88   126.9  1361.4   128.2 1360.66   129.3 1360.12   130.6 1359.95
   131.2 1359.85   132.6 1359.69   135.9 1359.52     138 1359.45   140.1 1359.38
   141.7 1359.29   142.5 1359.26   145.8 1359.04   155.7 1358.06     159 1357.84
   160.3 1357.79   163.1 1357.66   165.8 1357.45   168.8 1357.14   169.3 1357.06
   170.8 1356.71   171.3 1356.62   172.9  1356.1   173.8 1355.47   175.8 1353.73
   176.3 1353.27   176.5 1353.04     177  1352.5   178.8 1350.49     180 1349.27
  180.11 1349.21  187.94 1346.53  192.48 1345.34  201.68 1345.03  210.62 1343.31
  219.36 1343.69  227.01 1343.72  231.86  1344.3  236.82 1346.18   238.3 1346.25
   238.8 1347.59   239.2 1347.89   240.7 1349.07   241.3 1349.53   242.7 1350.67
   243.8 1351.45   244.2 1351.78   245.4  1352.3   246.3 1352.75   247.8  1353.4
   248.8 1353.59   251.1 1353.96   251.3 1353.99   251.6 1354.03   258.3 1354.75
   264.9 1355.39   265.8 1355.49   266.1 1355.52   266.8 1355.59   268.6 1355.76
   269.5 1355.85   271.1 1355.95     272    1356   273.1 1356.06   273.5 1356.06
   280.4 1355.85   281.8 1356.06   283.3 1356.44   284.1 1356.76   285.8 1357.98
   286.2 1358.36   287.7 1359.73   288.2 1360.36   289.3 1361.88   290.7 1364.03
   291.4 1365.13   293.1 1367.86   293.3 1368.03     295 1370.45   295.6 1371.13
   296.8 1372.25   298.1 1373.24   298.7  1373.7   300.4  1374.9     303 1376.74
   304.3 1377.76   305.4 1378.59     306    1379   307.5 1380.08   307.9 1380.35
   309.6 1381.53   312.8 1383.37   313.2 1383.63   314.6  1384.4   315.2 1384.76
   316.9 1385.71   317.7 1386.16   319.3 1387.06   320.1 1387.56   320.5 1387.82
   322.6 1389.16   324.2 1390.25   325.1 1390.82   327.8 1392.67     330 1394.03
   331.5 1395.06   335.1 1397.36   335.9 1397.83   337.3 1398.65   338.8 1399.62
   339.8 1400.32   341.8 1401.87   342.4 1402.27     343 1402.62   344.7 1403.59
   346.1 1404.45   347.1    1405   349.3 1406.08   353.4 1407.98   354.5 1408.72
   356.8 1410.11     357  1410.2     357 1410.24   357.2  1410.4   359.4  1412.2
   360.7 1413.05   361.9 1413.94   364.3 1415.43   364.3 1415.44   364.3 1415.45
   366.8 1417.23     368 1417.97   369.1 1418.81
BR D #Mann= 5
       0     .04  187.94     .04   238.3      .1   258.3    .016   285.8      .1
BC Design=,, 0 ,, 0 ,,,,,,
BC Use User HTab Curves=0
BC User HTab FreeFlow(D)= 0

Type RM Length L Ch R = 1 ,6876    ,92.2,101.9,105.6
BEGIN DESCRIPTION:
Channel burn from 54089LIC038BD
END DESCRIPTION:
XS GIS Cut Line= 4
2002011.15777245286957.7712939722001993.36045972287119.928977276
 2001956.0473368287207.4538304582001907.56727256287307.087177208
#Sta/Elev= 30
       0 1371.14    92.5 1366.77   119.4 1364.15   122.7 1363.66   129.3 1360.12
   171.3 1356.62   173.8 1355.47     180 1349.27  187.94 1346.53  192.48 1345.34
  201.68 1345.03  210.62 1343.31  227.01 1343.72   238.3 1346.25   238.8 1347.59
   242.7 1350.67   247.8  1353.4   258.3 1354.75   273.1 1356.06   280.4 1355.85
   283.3 1356.44   285.8 1357.98   288.2 1360.36     295 1370.45   298.7  1373.7
   309.6 1381.53   320.1 1387.56   342.4 1402.27     357  1410.2   369.1 1418.81
#Mann= 5 ,-1 , 0
       0     .04       0  187.94    .045       0   238.3      .1       0
   258.3    .016       0   285.8      .1       0
#XS Ineff= 2 , 0
        175.6667  1353.5244.3333          1353.5
Permanent Ineff=
       F       F
#Block Obstruct= 2 ,-1
       0    16.3 1389.79   22.32  108.81 1388.83
Bank Sta=187.94,238.3
XS Rating Curve= 0 ,0
Exp/Cntr(USF)=0,0
Exp/Cntr=0.5,0.3

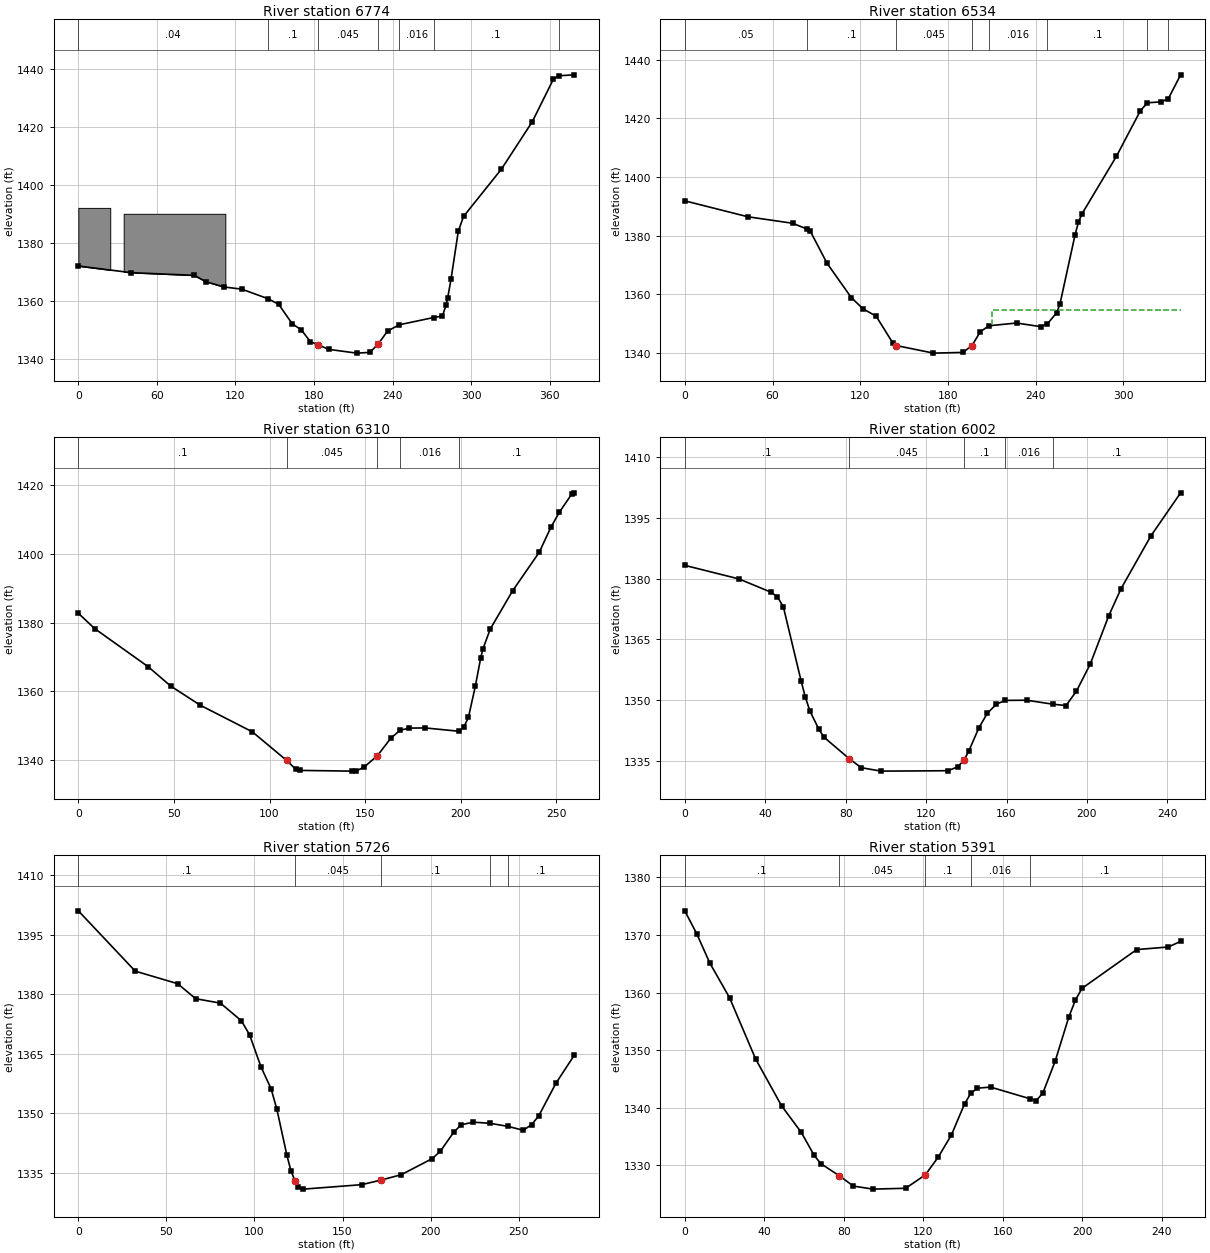
Type RM Length L Ch R = 1 ,6774    ,225.5,239.5,246.5
XS GIS Cut Line= 2
2002009.69074661286945.422060948  2001789.311505287253.411083038
#Sta/Elev= 30
       0 1372.06    40.1 1369.78    88.5 1368.85    97.4 1366.66   111.5 1364.83
   124.8  1364.1     145 1360.79     153 1358.89   163.3 1352.23   170.3 1350.09
   177.2 1346.05   183.2 1344.89   191.5 1343.37   212.6 1342.09   222.7 1342.34
   229.1 1345.27   236.2  1349.7   245.2 1351.85   271.4 1354.34   278.1 1354.85
   280.8 1358.55   282.1 1361.05   284.7 1367.67   290.2 1384.01   294.2  1389.1
   323.2 1405.42   346.7 1421.69   362.8  1436.3   366.8  1437.5   378.7 1437.83
#Mann= 7 ,-1 , 0
       0     .04       0     145      .1       0   183.2    .045       0
   229.1      .1       0   245.2    .016       0   271.4      .1       0
   366.8    .016       0
#Block Obstruct= 2 ,-1
       0   24.37 1392.06   34.64  112.28 1390.02
Bank Sta=183.2,229.1
XS Rating Curve= 0 ,0
Exp/Cntr(USF)=0,0
Exp/Cntr=0.3,0.1

Type RM Length L Ch R = 1 ,6534    ,223.4,224.4,225.3
XS GIS Cut Line= 3
2001861.90474296286850.3501506132001598.97229347287034.815848166
 2001583.3833612287043.870164783
#Sta/Elev= 30
       0 1391.88    43.2 1386.44    73.8 1384.23    83.3 1382.32    85.9 1381.47
    97.4 1370.53   113.9 1358.91     122 1355.04   130.9 1352.57   142.1 1343.59
   144.5 1342.57   170.1 1339.97   190.1 1340.21   196.3 1342.42   202.2 1347.29
   208.1  1349.3     227 1350.23   243.4    1349   248.1 1349.92   254.3 1353.72
   256.6 1356.59     267 1380.34   269.3  1384.6   271.7 1387.43   295.3 1407.08
   311.7 1422.61   316.5  1425.3   326.1 1425.63   330.8 1426.72   339.2 1434.83
#Mann= 8 ,-1 , 0
       0     .05       0    83.3      .1       0   144.5    .045       0
   196.3      .1       0   208.1    .016       0   248.1      .1       0
   316.5    .016       0   330.8      .1       0
#XS Ineff= 2 , 0
                             210         1354.52
Permanent Ineff=
       F       F
Bank Sta=144.5,196.3
XS Rating Curve= 0 ,0
Exp/Cntr(USF)=0,0
Exp/Cntr=0.3,0.1

Type RM Length L Ch R = 1 ,6310    ,313.7,307.9,304.4
XS GIS Cut Line= 2
2001691.20514224286704.4295241912001472.32420261286843.467102197
#Sta/Elev= 30
       0 1382.72     8.5 1378.27    36.6 1367.11    48.3  1361.5    63.8 1355.91
      91 1348.16   108.9 1339.84   113.6 1337.32     116 1336.92   143.1 1336.71
   145.4  1336.8   149.3 1337.81   156.4 1341.21   163.5 1346.35   168.3 1348.63
   173.1 1349.25   181.4  1349.3   199.2 1348.32   201.6 1349.52     204 1352.38
   207.6 1361.39   210.4 1369.61   211.5 1372.19   215.4  1378.1   227.1 1389.26
     241 1400.46   247.1 1407.72   251.5 1412.12   258.1 1417.51   259.3 1417.82
#Mann= 5 ,-1 , 0
       0      .1       0   108.9    .045       0   156.4      .1       0
   168.3    .016       0   199.2      .1       0
Bank Sta=108.9,156.4
XS Rating Curve= 0 ,0
Exp/Cntr(USF)=0,0
Exp/Cntr=0.3,0.1

Type RM Length L Ch R = 1 ,6002    ,283.6,276.3,268.4
XS GIS Cut Line= 2
 2001457.1814961286470.4058780432001274.09240823 286635.59904003
#Sta/Elev= 30
       0 1383.28    26.9 1379.93    42.7 1376.68      46 1375.54      49 1373.06
    57.8 1354.79    59.9 1350.77    62.2 1347.29    66.7  1342.7    69.2 1340.79
    81.9 1335.41    87.8 1333.24    97.6 1332.39   130.9 1332.49   135.8 1333.47
   138.9 1335.15   141.2 1337.29   146.2 1343.03   150.4 1346.65     155 1348.97
   159.5 1349.88     170 1349.93   183.1 1348.94   189.6 1348.61   194.8 1352.18
   201.6 1358.82   210.9 1370.86   216.9 1377.45   231.8 1390.56   246.6 1401.22
#Mann= 5 ,-1 , 0
       0      .1       0    81.9    .045       0   138.9      .1       0
   159.5    .016       0   183.1      .1       0
Bank Sta=81.9,138.9
XS Rating Curve= 0 ,0
Exp/Cntr(USF)=0,0
Exp/Cntr=0.3,0.1

Type RM Length L Ch R = 1 ,5726    ,350.9,334.9,315.3
Node Name=B
XS GIS Cut Line= 2
2001257.57309203286236.3822318942001095.13314941286466.276048993
#Sta/Elev= 30
       0    1401    32.3  1385.8    56.4 1382.63    66.6 1378.85    80.7 1377.73
    92.6 1373.27    97.2 1369.77   103.7 1361.66   109.4 1356.18   112.7 1351.01
   118.4 1339.39   120.7 1335.49   123.1  1332.8   124.7  1331.3   127.8 1330.85
   160.8 1331.97     172 1333.15   183.3 1334.48   200.8 1338.51   205.5 1340.38
   213.1 1345.18   217.4 1347.07   224.3 1347.73   233.7 1347.44   243.8 1346.68
   252.6 1345.69   257.3 1347.09   261.3 1349.25   271.1  1357.5   281.5 1364.56
#Mann= 5 ,-1 , 0
       0      .1       0   123.1    .045       0     172      .1       0
   233.7    .016       0   243.8      .1       0
Bank Sta=123.1,172
XS Rating Curve= 0 ,0
Exp/Cntr(USF)=0,0
Exp/Cntr=0.3,0.1

Type RM Length L Ch R = 1 ,5391    ,250.4,244.4,232.8
XS GIS Cut Line= 2
2000866.61594199286138.6429443852000856.97967421286387.809297049
#Sta/Elev= 30
       0  1374.2       6 1370.22    12.6 1365.12    22.5 1359.12    35.6 1348.49
    48.7 1340.33    58.6 1335.72    65.1 1331.72    68.4  1330.3    77.7 1328.19
    84.8  1326.4    94.7 1325.87   111.1 1326.02     121 1328.35   127.5 1331.44
   134.1 1335.27   140.7 1340.66   143.9 1342.53   147.2  1343.4   153.8 1343.59
   173.4 1341.59   176.8 1341.25   180.1 1342.55   186.3  1348.1   193.2  1355.8
   196.5 1358.71   199.8 1360.74   227.3 1367.47   243.2 1367.92   249.4  1368.9
#Mann= 5 ,-1 , 0
       0      .1       0    77.7    .045       0     121      .1       0
   143.9    .016       0   173.4      .1       0
Bank Sta=77.7,121
XS Rating Curve= 0 ,0
Exp/Cntr(USF)=0,0
Exp/Cntr=0.3,0.1

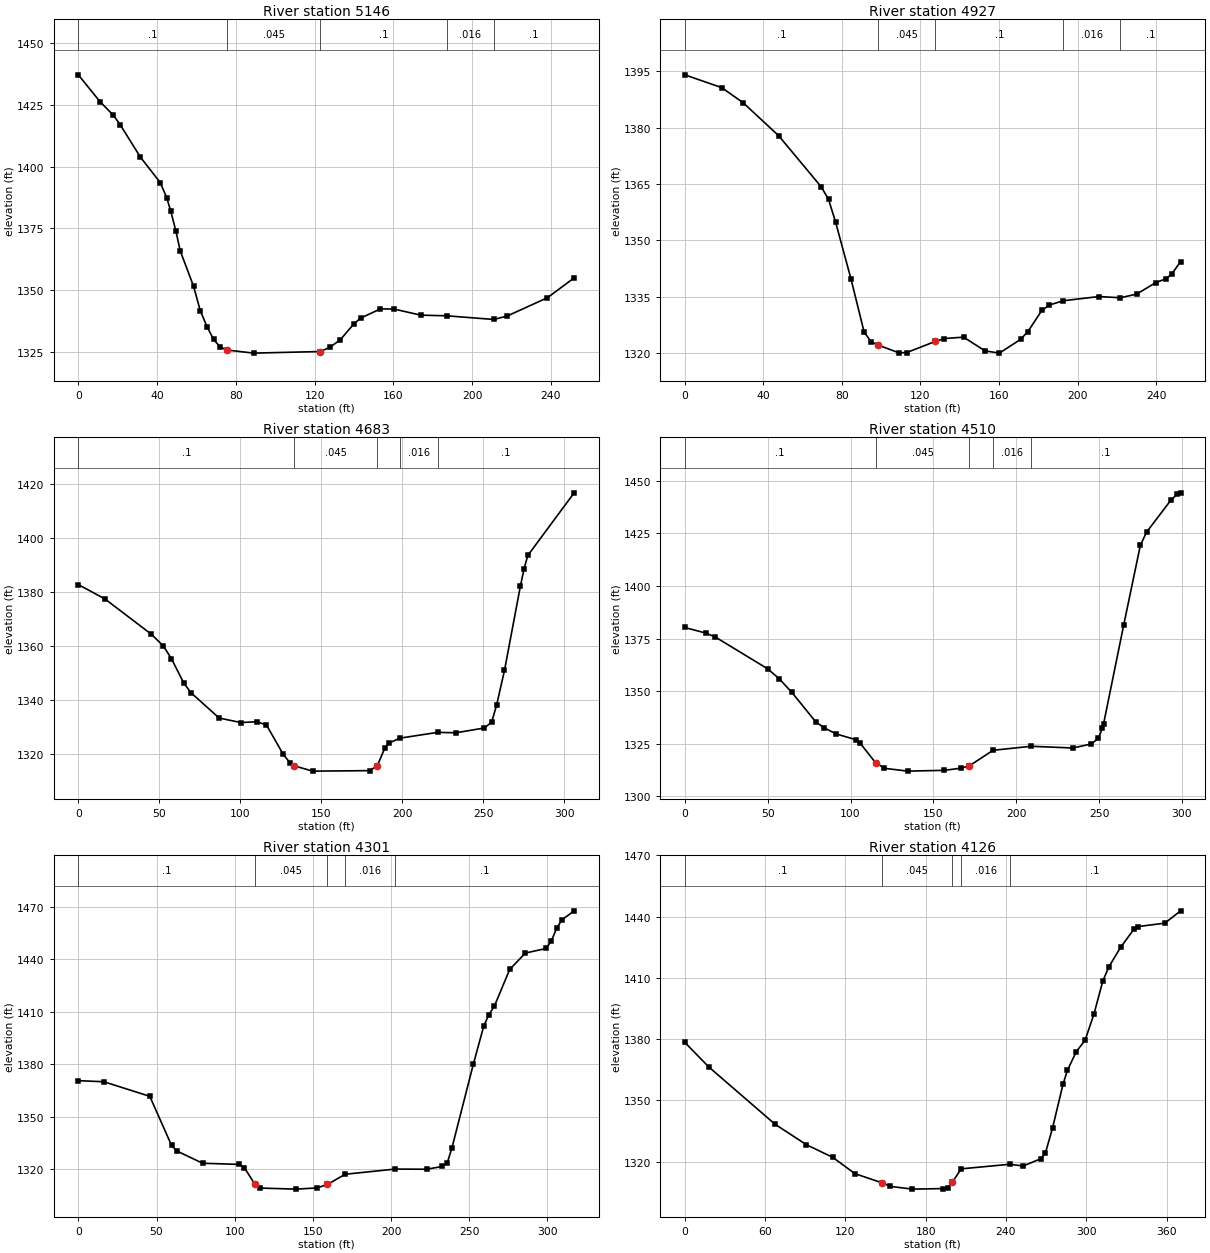
Type RM Length L Ch R = 1 ,5146    ,223.9,218.9,211.7
XS GIS Cut Line= 2
2000596.80044408286137.2663347012000660.12448951286380.926248633
#Sta/Elev= 30
       0 1437.16      11  1426.3    17.8 1420.81    21.2 1417.05    31.4 1403.99
    41.6 1393.55    44.9 1387.43    46.9 1382.07    49.6 1373.78    51.7 1366.03
    58.5 1351.64    61.9 1341.79    65.3  1335.3    68.7 1330.06    72.1 1326.99
    75.5  1325.8      89 1324.54   122.9 1325.19   127.6 1326.84     133  1329.9
   139.9 1336.36   143.3 1338.69   153.4 1342.43   160.2  1342.4   173.8 1339.92
   187.3 1339.63     211 1338.16   217.8 1339.56   238.2 1346.95   251.8 1354.99
#Mann= 5 ,-1 , 0
       0      .1       0    75.5    .045       0   122.9      .1       0
   187.3    .016       0     211      .1       0
Bank Sta=75.5,122.9
XS Rating Curve= 0 ,0
Exp/Cntr(USF)=0,0
Exp/Cntr=0.3,0.1

Type RM Length L Ch R = 1 ,4927    ,206.9,244.4,273.7
XS GIS Cut Line= 2
 2000373.7896754286212.9798672792000481.16523069286441.497074695
#Sta/Elev= 30
       0 1394.06    18.8 1390.65    29.7 1386.64    47.8 1377.85    69.5 1364.23
    73.2  1360.9    76.8 1354.84    84.6 1339.79    91.3 1325.64    94.9 1322.96
    98.5 1322.11     109 1320.07     113 1320.13   127.5 1323.08   132.2 1323.87
     142 1324.23   152.9 1320.58   160.2 1319.98     171 1323.64   174.7  1325.7
   181.9  1331.4   185.7 1332.79   192.8 1333.93   210.9 1335.04   221.8 1334.72
   230.1 1335.69   239.9 1338.77   244.9 1339.74   247.9 1340.98   252.5 1344.35
#Mann= 5 ,-1 , 0
       0      .1       0    98.5    .045       0   127.5      .1       0
   192.8    .016       0   221.8      .1       0
Bank Sta=98.5,127.5
XS Rating Curve= 0 ,0
Exp/Cntr(USF)=0,0
Exp/Cntr=0.3,0.1

Type RM Length L Ch R = 1 ,4683    ,161.4,173,183.6
XS GIS Cut Line= 2
 2000307.7124106 286204.72020918 2000102.5975678286431.860806912
#Sta/Elev= 30
       0 1382.68    16.4 1377.38    45.1 1364.27    52.5 1359.92    57.4  1355.3
      65 1346.31    69.4 1342.69    86.9 1333.24   100.3 1331.57   110.2 1331.87
   116.1 1330.67   126.4 1319.85   130.8 1316.53   133.4  1315.5   144.6 1313.57
   179.9 1313.75   184.5 1315.57   189.1 1322.06   191.5 1323.92   198.4 1325.78
   221.7 1327.93     233 1327.77   250.6 1329.56   255.1 1331.75   258.1 1337.95
     263 1350.89   272.8 1382.07   275.1 1388.61   277.4 1393.49     306 1416.69
#Mann= 5 ,-1 , 0
       0      .1       0   133.4    .045       0   184.5      .1       0
   198.4    .016       0   221.7      .1       0
Bank Sta=133.4,184.5
XS Rating Curve= 0 ,0
Exp/Cntr(USF)=0,0
Exp/Cntr=0.3,0.1

Type RM Length L Ch R = 1 ,4510    ,198.5,208.7,215.7
XS GIS Cut Line= 2
2000227.86904897286117.9937991361999962.18338011286255.654767459
#Sta/Elev= 30
       0 1380.27    12.5 1377.65    18.3  1375.8      50 1360.62    56.9 1355.95
    64.6 1349.41      79 1335.42      84  1332.6    91.3 1329.66   103.5 1326.84
   105.9 1325.18   115.1 1315.97   120.5  1313.3   134.5 1311.96   156.6 1312.34
   166.8 1313.38   171.7 1314.46     186 1321.87     209 1323.78   234.2 1322.96
   245.3 1324.88   249.5 1327.55     252 1332.32   252.7 1334.41   264.8 1381.26
   274.9 1419.38   278.7 1425.69   293.4 1440.91     297  1443.6   299.2 1444.32
#Mann= 5 ,-1 , 0
       0      .1       0   115.1    .045       0   171.7      .1       0
     186    .016       0     209      .1       0
Bank Sta=115.1,171.7
XS Rating Curve= 0 ,0
Exp/Cntr(USF)=0,0
Exp/Cntr=0.3,0.1

Type RM Length L Ch R = 1 ,4301    ,164.4,175.1,182.2
XS GIS Cut Line= 2
2000150.77890671285973.4497823971999838.28850862286027.137560043
#Sta/Elev= 30
       0 1370.66    16.3 1370.04    45.7 1361.73    59.6 1333.74    62.9 1330.54
    79.5 1323.52   102.8 1322.87   106.2 1320.98   112.8 1311.68   116.2 1309.36
   139.4 1308.75   152.8 1309.45   159.3 1311.42   170.7 1317.25   202.7  1320.2
   222.7  1320.1   232.7 1321.67     236 1323.93   238.9 1332.16   252.6 1379.99
   259.3 1401.87   262.6 1408.39     266 1413.04   275.9 1434.18   285.9 1443.49
   299.2 1446.12   302.6  1450.6   305.9  1457.6   309.2 1462.41   317.1  1467.6
#Mann= 5 ,-1 , 0
       0      .1       0   112.8    .045       0   159.3      .1       0
   170.7    .016       0   202.7      .1       0
Bank Sta=112.8,159.3
XS Rating Curve= 0 ,0
Exp/Cntr(USF)=0,0
Exp/Cntr=0.3,0.1

Type RM Length L Ch R = 1 ,4126    ,204.3,207.5,208.7
XS GIS Cut Line= 2
2000175.55788101 285846.801691541999808.00309559285799.996962311
#Sta/Elev= 30
       0  1378.4      18 1366.34    67.6 1338.27    90.8 1328.37   110.6 1322.13
   127.2 1314.14     147 1309.77   153.6 1307.93   170.1  1306.6   193.3 1306.87
   196.6 1307.32   199.9 1309.92   206.5 1316.52   242.9 1318.77   252.8 1317.91
   266.1  1321.5   269.4 1324.12   274.8 1336.51   282.6  1357.9   285.9  1364.7
   292.5 1373.86   299.1 1379.43   305.7  1392.2   312.4 1408.55     317 1415.51
   325.6 1424.88   335.5 1433.68   338.8 1435.09   358.7 1436.76   370.5 1442.79
#Mann= 5 ,-1 , 0
       0      .1       0     147    .045       0   199.9      .1       0
   206.5    .016       0   242.9      .1       0
Bank Sta=147,199.9
XS Rating Curve= 0 ,0
Exp/Cntr(USF)=0,0
Exp/Cntr=0.3,0.1