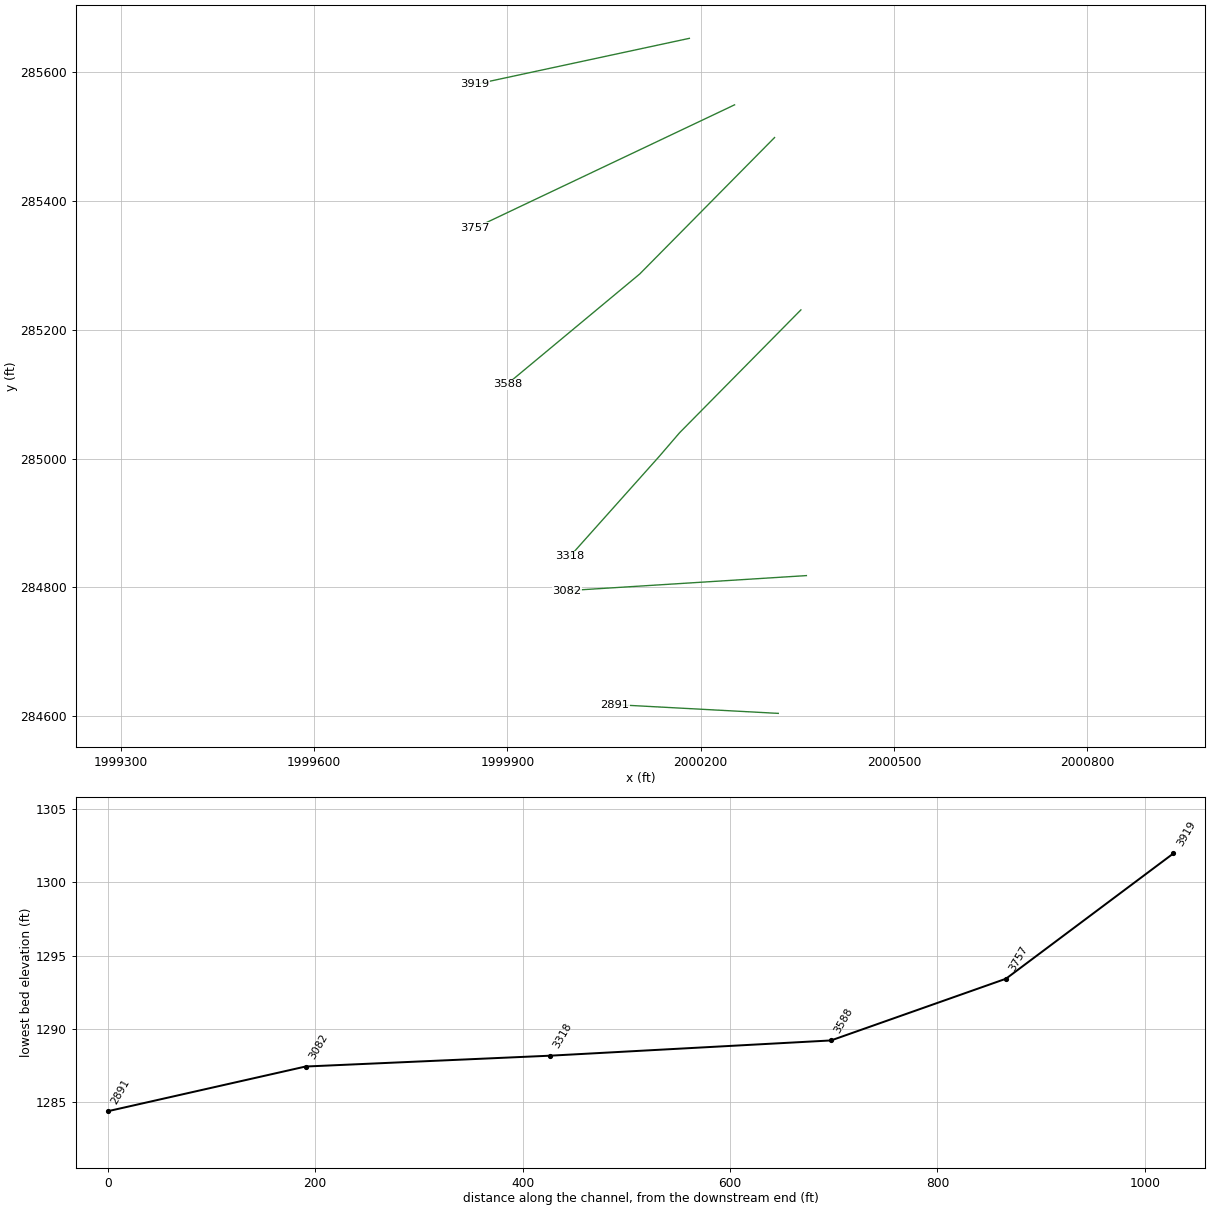
HEC-RAS study LICKCK2_AE.prj: LICKCK2_AE

--- LICKCK2_AE.g01 (geometry) --- (continued)

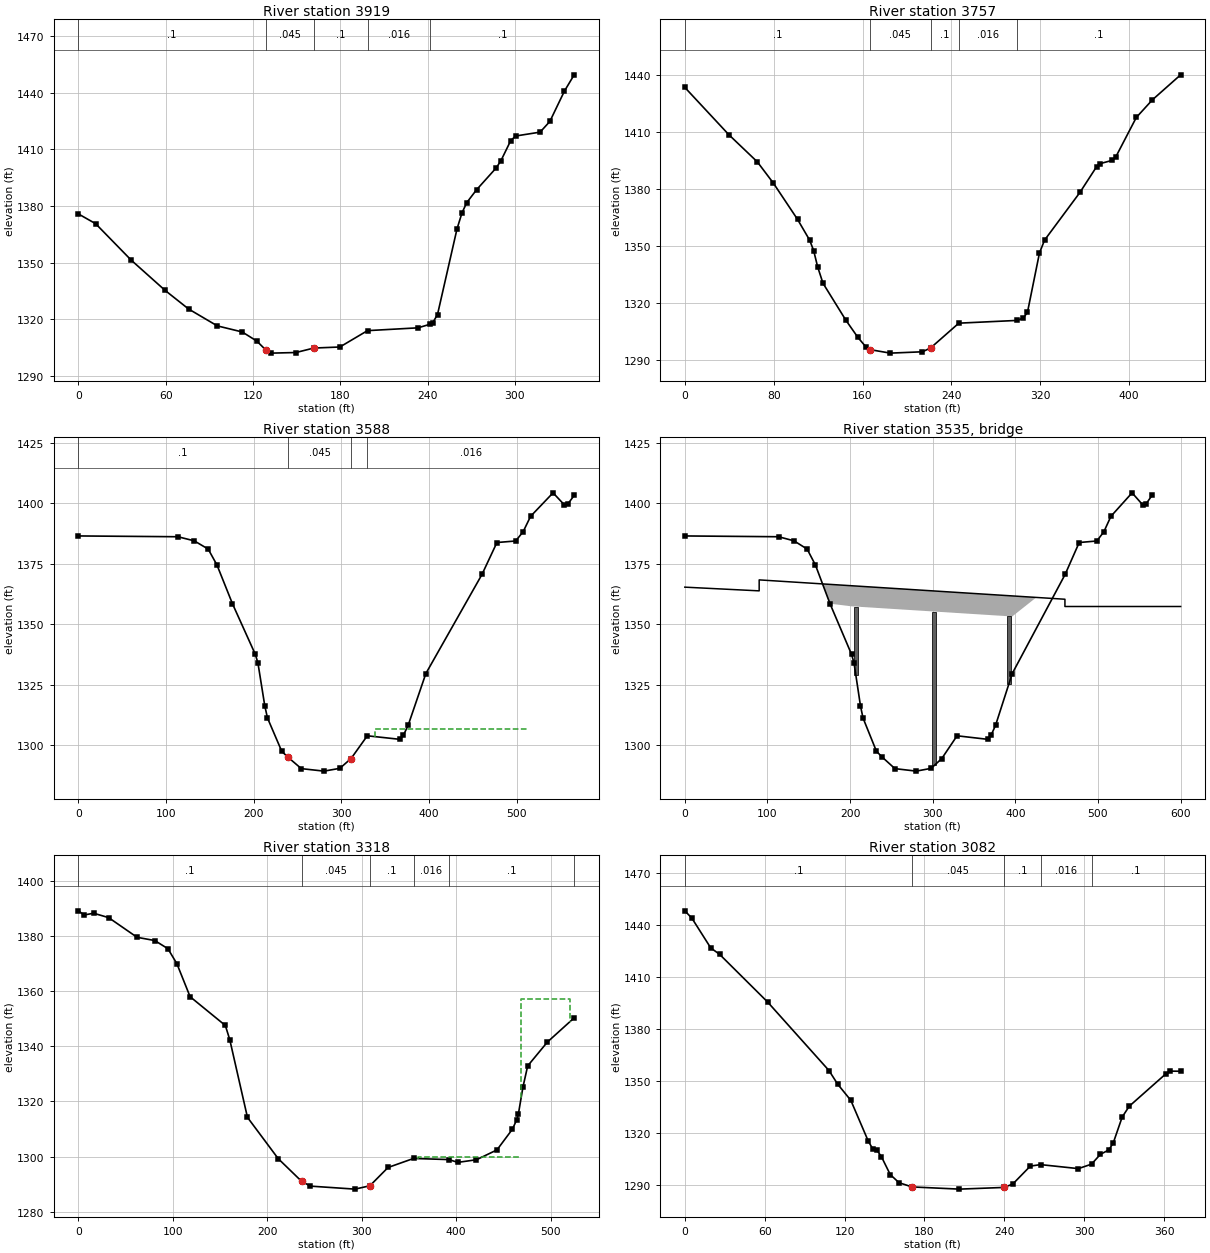
Type RM Length L Ch R = 1 ,3919    ,153.1,161.5,168.1
XS GIS Cut Line= 2
2000182.44092943285652.6997262051999849.30138609285581.116022677
#Sta/Elev= 30
       0 1375.83    11.9 1370.62    36.3 1351.32    59.6 1335.26    75.7 1325.41
    95.5 1316.42   112.6  1313.2   122.6 1308.39   128.7 1303.73   132.7 1301.97
   149.5 1302.29   161.8 1304.66   179.7 1305.22   198.7  1313.9   233.4 1315.39
   241.9 1317.34   243.4 1317.91   246.8 1322.45   260.2 1367.85   263.6 1376.33
   266.9 1381.82   273.6  1388.6   287.1  1400.2   290.4 1404.07   297.1 1414.69
   300.5 1417.15   317.3  1419.2     324 1424.88     334 1440.95   340.7  1449.6
#Mann= 5 ,-1 , 0
       0      .1       0   128.7    .045       0   161.8      .1       0
   198.7    .016       0   241.9      .1       0
Bank Sta=128.7,161.8
XS Rating Curve= 0 ,0
Exp/Cntr(USF)=0,0
Exp/Cntr=0.3,0.1

Type RM Length L Ch R = 1 ,3757    ,153.1,168.7,179.2
XS GIS Cut Line= 2
2000252.64802327285549.4539999631999849.30138609285358.105253994
#Sta/Elev= 30
       0 1433.46    39.7  1408.5    65.3 1394.21    79.7 1383.05   101.5 1363.91
   112.4 1352.97     116 1347.48   119.6 1338.89   124.4 1330.26     145 1310.78
   155.9 1301.66   163.2  1296.6   166.8 1295.26     185 1293.42     214 1294.13
   221.3 1296.15   246.7 1309.21   299.3 1310.66   304.8 1311.97   308.5 1314.91
   319.3 1346.17   323.9 1352.97   355.7 1378.07   370.7 1391.63   373.8 1393.27
   384.7 1394.99     388 1396.79   406.5 1417.61     421 1426.91   446.4 1440.08
#Mann= 5 ,-1 , 0
       0      .1       0   166.8    .045       0   221.3      .1       0
   246.7    .016       0   299.3      .1       0
Bank Sta=166.8,221.3
XS Rating Curve= 0 ,0
Exp/Cntr(USF)=0,0
Exp/Cntr=0.5,0.3

Type RM Length L Ch R = 1 ,3588    ,270.5,270.8,290.2
BEGIN DESCRIPTION:
Channel burned from 54089LIC032BU
END DESCRIPTION:
XS GIS Cut Line= 3
2000314.73311999285498.6571026522000105.35078717285286.796872403
1999899.68530049285115.821949746
#Sta/Elev= 30
       01386.398 113.5811386.067 132.1411384.375 148.0311380.977 158.068 1374.39
 175.7081358.402 201.7391337.501 204.7421333.983  212.611316.125 215.6591311.181
 231.898 1297.42  239.06 1294.94  254.27 1290.24  280.09 1289.21  298.12 1290.36
  310.99 1294.42 329.4681303.813 366.333 1302.36   370.61304.025 376.0631308.154
 396.1981329.511 460.1961370.472 477.261 1383.68 498.5941384.313 507.1271388.127
  515.661394.509 541.2591404.215 554.0581399.273 557.781 1399.45 565.3211403.127
#Mann= 4 ,-1 , 0
       0      .1       0  239.06    .045       0  310.99      .1       0
 329.468    .016       0
#XS Ineff= 3 ,-1
       0      37 1385.98   338.7     513 1306.56     513     600 1385.98
Permanent Ineff=
       F       F       F
Bank Sta=239.06,310.99
XS Rating Curve= 0 ,0
Exp/Cntr(USF)=0,0
Exp/Cntr=0.5,0.3

Type RM Length L Ch R = 3 ,3535    ,,,
BEGIN DESCRIPTION:
I-64
Bridge Survey ID: 54089LIC030
Include 3 ft railing
END DESCRIPTION:
Bridge Culvert--1,0,-1,-1, 0
Deck Dist Width WeirC Skew NumUp NumDn MinLoCord MaxHiCord MaxSubmerge Is_Ogee
53,178,2.6,0, 6, 6, , , 0.98, 0, 0,0,,
       0      90      90     460     460     600
1365.2361363.7051368.2361360.2421357.2421357.242
                1359.7361351.742
       0      90      90     460     460     600
1365.2361363.7051368.2361360.2421357.2421357.242
                1359.7361351.742
Pier Skew, UpSta & Num, DnSta & Num=  ,207, 2 ,232, 2 , 0 , 0 , 0 ,,
       5       5
       0    1360
       5       5
       0    1360
Pier Skew, UpSta & Num, DnSta & Num=  ,302, 2 ,322, 2 , 0 , 0 , 0 ,,
       5       5
       0    1360
       5       5
       0    1360
Pier Skew, UpSta & Num, DnSta & Num=  ,392, 2 ,411, 2 , 0 , 0 , 0 ,,
       5       5
       0    1360
       5       5
       0    1360
BR Coef=-1 , 1 , 0 ,0.9, 0 ,,,0.8,0,1.2,0,
WSPro=,,,, 1 ,,,, 0 ,,,, 0 ,,,,-1 ,-1 ,-1 , 0 , 0 , 0 , 0 , 0
BR U #Sta/Elev= 30
       01386.398 113.5811386.067 132.1411384.375 148.0311380.977 158.068 1374.39
 175.7081358.402 201.7391337.501 204.7421333.983  212.611316.125 215.6591311.181
 231.898 1297.42  239.06 1294.94  254.27 1290.24  280.09 1289.21  298.12 1290.36
  310.99 1294.42 329.4681303.813 366.333 1302.36   370.61304.025 376.0631308.154
 396.1981329.511 460.1961370.472 477.261 1383.68 498.5941384.313 507.1271388.127
  515.661394.509 541.2591404.215 554.0581399.273 557.781 1399.45 565.3211403.127
BR U #Mann= 4
       0      .1  239.06     .04  310.99      .1 329.468    .016
BR D #Sta/Elev= 30
       0 1389.14     6.2 1387.63    16.2 1388.27    32.1 1386.67    62.2 1379.53
    80.9 1378.36    94.8  1375.4   104.3 1369.96   118.3 1357.98   155.6 1347.54
   160.3 1342.38     179 1314.21   211.6 1299.21   236.3 1291.01   245.6 1289.26
   292.8 1288.17   308.61289.387   327.8 1296.02   354.8  1299.3   392.1 1298.89
   401.7 1297.88   421.4 1298.83   443.1  1302.4   459.4 1309.89     464 1313.32
   465.7 1315.27   470.6  1325.2   475.6 1332.87   496.5 1341.54   524.8 1350.31
BR D #Mann= 6
       0      .1   236.3     .04   308.6      .1   354.8    .016   392.1      .1
   524.8    .016
BC Design=,, 0 ,, 0 ,,,,,,
BC Use User HTab Curves=0
BC User HTab FreeFlow(D)= 0

Type RM Length L Ch R = 1 ,3318    ,260.8,235.9,190.7
XS GIS Cut Line= 4
2000355.61842758285231.0441802322000167.30408266285040.355385638
2000135.73862342285003.6321405941999996.94591712284848.209027327
#Sta/Elev= 30
       0 1389.14     6.2 1387.63    16.2 1388.27    32.1 1386.67    62.2 1379.53
    80.9 1378.36    94.8  1375.4   104.3 1369.96   118.3 1357.98   155.6 1347.54
   160.3 1342.38     179 1314.21   211.6 1299.21   236.3 1291.01   245.6 1289.26
   292.8 1288.17   308.61289.387   327.8 1296.02   354.8  1299.3   392.1 1298.89
   401.7 1297.88   421.4 1298.83   443.1  1302.4   459.4 1309.89     464 1313.32
   465.7 1315.27   470.6  1325.2   475.6 1332.87   496.5 1341.54   524.8 1350.31
#Mann= 6 ,-1 , 0
       0      .1       0   236.3    .045       0   308.6      .1       0
   354.8    .016       0   392.1      .1       0   524.8    .016       0
#XS Ineff= 3 ,-1
       081.33334 1358.21     360468.6667    1300468.6667     520 1357.27
Permanent Ineff=
       F       F       F
Bank Sta=236.3,308.6
XS Rating Curve= 0 ,0
Exp/Cntr(USF)=0,0
Exp/Cntr=0.5,0.3

Type RM Length L Ch R = 1 ,3082    ,196.7,190.7,187.5
Node Name=A
XS GIS Cut Line= 2
2000364.15340761284818.4742581691999992.46879314284795.071893554
#Sta/Elev= 30
       0 1448.36     5.3 1444.13    19.5  1426.9    26.1 1423.23    62.2 1395.63
   108.3 1355.99   114.8 1348.15   124.7 1338.76   137.8 1315.19   141.1 1310.78
   144.4 1309.85   147.7 1306.14   154.3 1295.86   160.9 1291.14   170.7  1288.7
   206.3 1287.43   239.7 1288.41   246.3 1290.34   259.5 1300.74   267.2  1301.6
   295.6 1299.29   305.5 1301.88   312.1 1307.52   318.6 1310.16   321.9 1314.37
   328.5  1329.1   333.8 1335.36   361.4 1354.17   364.7 1355.66   372.4 1355.59
#Mann= 5 ,-1 , 0
       0      .1       0   170.7    .045       0   239.7      .1       0
   267.2    .016       0   305.5      .1       0
Bank Sta=170.7,239.7
XS Rating Curve= 0 ,0
Exp/Cntr(USF)=0,0
Exp/Cntr=0.3,0.1

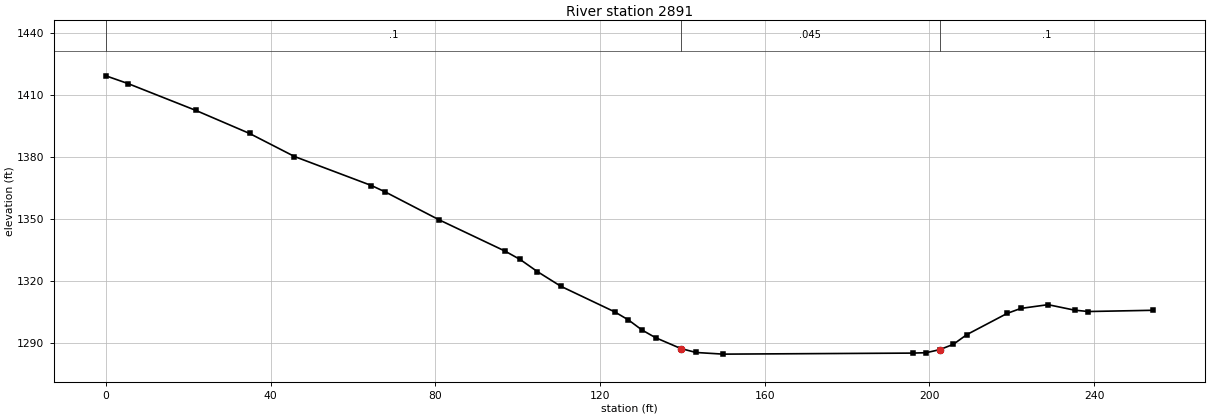
Type RM Length L Ch R = 1 ,2891    ,210.2,204.7,200.3
XS GIS Cut Line= 2
2000320.51488065284604.549113395 2000066.5303941284618.177549259
#Sta/Elev= 30
       0 1419.39     5.4 1415.61    21.8 1402.65    34.9 1391.42    45.8 1380.25
    64.5 1366.16    67.8  1363.1    80.9 1349.55    96.9 1334.39   100.6 1330.29
   104.8  1324.4   110.5 1317.28   123.6 1304.84   126.9 1300.96   130.2 1296.07
   133.5 1292.34   139.6 1287.11   143.3 1285.18   149.9 1284.38   195.9 1284.88
   199.2 1285.07   202.5 1286.56   205.8 1289.15   209.1 1293.87   218.9 1304.17
   222.2 1306.56   228.8 1308.37   235.3 1305.69   238.6 1305.05   254.3 1305.65
#Mann= 3 ,-1 , 0
       0      .1       0   139.6    .045       0   202.5      .1       0
Bank Sta=139.6,202.5
XS Rating Curve= 0 ,0
Exp/Cntr(USF)=0,0
Exp/Cntr=0.3,0.1