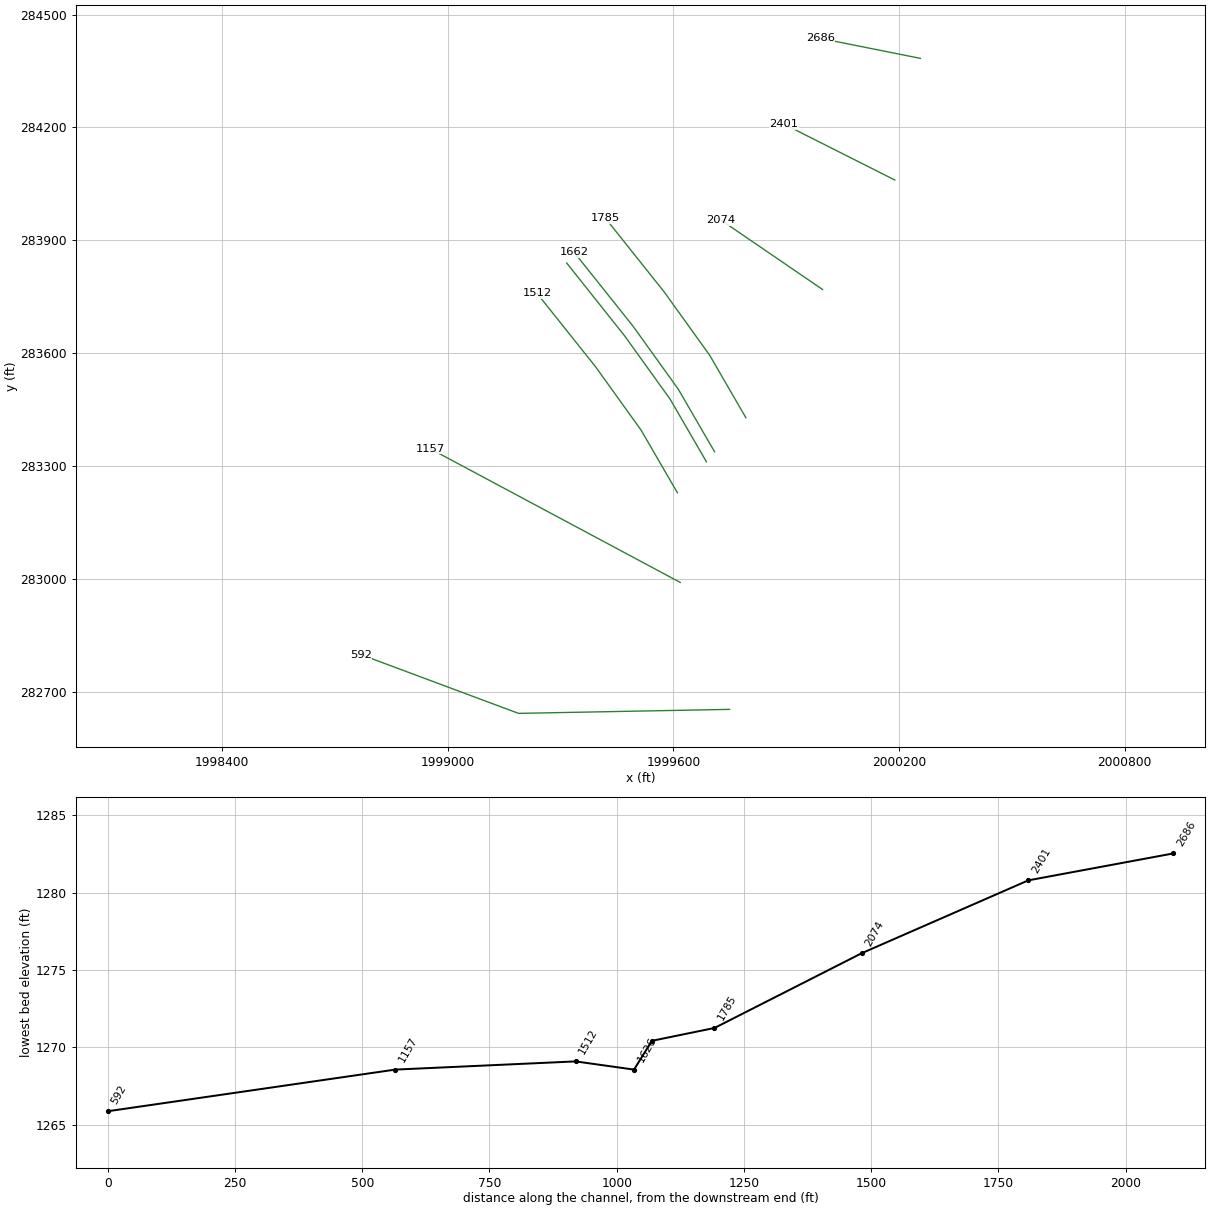
HEC-RAS study LICKCK2_AE.prj: LICKCK2_AE

--- LICKCK2_AE.g01 (geometry) --- (continued)

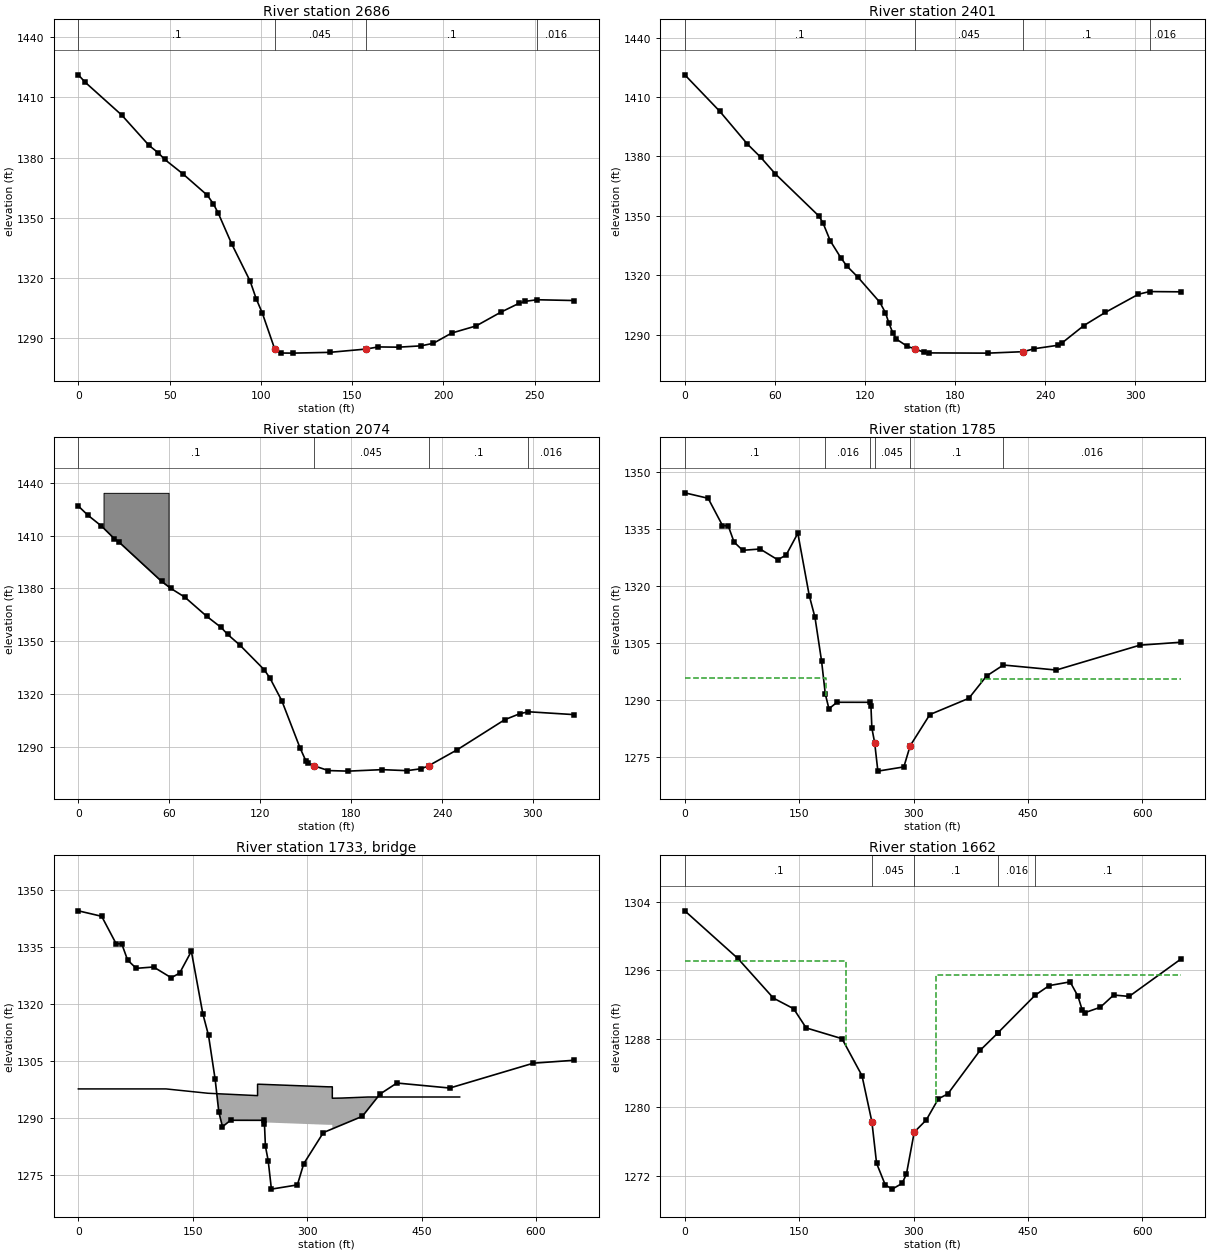
Type RM Length L Ch R = 1 ,2686    ,294.9,285.1,273.7
XS GIS Cut Line= 2
2000256.50253038284383.6032592371999990.12855668284436.878053978
#Sta/Elev= 30
       0 1421.27     3.7 1417.61    23.8 1401.18    38.7  1386.1    43.9  1382.3
    47.2 1379.18    57.3 1371.88    70.7  1361.2      74 1356.92    76.7  1352.2
      84    1337    94.1 1318.44    97.4 1309.72   100.8 1302.44   107.5  1284.8
   110.8  1282.6   117.5 1282.54   137.6 1282.92   157.6 1284.57   164.3 1285.63
   175.4 1285.51   187.8 1286.17   194.5 1287.46   204.5 1292.54   217.9  1296.1
   231.4 1302.93   241.3 1307.33   244.6 1308.33   251.3 1309.15   271.6 1308.76
#Mann= 4 ,-1 , 0
       0      .1       0   107.5    .045       0   157.6      .1       0
   251.3    .016       0
Bank Sta=107.5,157.6
XS Rating Curve= 0 ,0
Exp/Cntr(USF)=0,0
Exp/Cntr=0.3,0.1

Type RM Length L Ch R = 1 ,2401    ,331.5,327.5,319.3
XS GIS Cut Line= 2
2000188.36035106284060.2376446471999893.49055692284208.911490436
#Sta/Elev= 30
       0 1421.18    23.3 1402.77    41.7 1386.24    50.5 1379.63    60.3  1371.2
    89.5  1349.8    92.1 1346.34    96.9 1337.41   103.8 1329.03   107.8 1324.82
   115.2 1319.18   129.9 1306.44   133.6 1301.19     136  1295.8   138.5 1291.07
   140.9 1287.87   148.3 1284.16   153.1 1283.01   159.3 1281.21   162.8 1280.91
     202  1280.8   225.4 1281.53   232.8 1283.03   248.4 1284.75   251.1 1285.87
   265.8 1294.73   280.1 1301.36   302.1  1310.5   309.5 1311.85   330.2 1311.72
#Mann= 4 ,-1 , 0
       0      .1       0   153.1    .045       0   225.4      .1       0
   309.5    .016       0
Bank Sta=153.1,225.4
XS Rating Curve= 0 ,0
Exp/Cntr(USF)=0,0
Exp/Cntr=0.3,0.1

Type RM Length L Ch R = 1 ,2074    ,299.4,289.2,277.2
XS GIS Cut Line= 2
1999996.32330025283769.0846966441999726.23248041283953.688055165
#Sta/Elev= 30
       0 1426.87     6.3 1421.67    15.2 1415.55    23.7 1408.36    27.1 1406.17
    54.9 1384.06    61.1    1380    70.3 1375.04    84.7 1364.18    94.2 1357.85
    98.6 1353.82   106.6 1347.78   122.6 1333.83   126.4  1329.1   134.3 1316.09
   146.3  1289.3   150.3 1281.66   151.7  1280.5   155.6 1279.11     165  1276.4
   178.1 1276.09   200.4 1276.93   216.9 1276.36   226.4 1277.47   231.1 1279.11
     250 1288.23   281.4 1305.35   291.2 1308.71     297 1309.86   327.2 1308.23
#Mann= 4 ,-1 , 0
       0      .1       0   155.6    .045       0   231.1      .1       0
     297    .016       0
#Block Obstruct= 1 ,-1
   16.63   59.55  1434.4
Bank Sta=155.6,231.1
XS Rating Curve= 0 ,0
Exp/Cntr(USF)=0,0
Exp/Cntr=0.5,0.3

Type RM Length L Ch R = 1 ,1785    ,124,123,122.6
BEGIN DESCRIPTION:
Channel burned from 54089LIC022BU
END DESCRIPTION:
XS GIS Cut Line= 4
1999792.53162673283428.0618440521999696.22559951283594.236949846
1999575.08073719 283762.889953071999418.97319911283958.643850025
#Sta/Elev= 30
       0 1344.49    30.6 1343.05    49.4 1335.89      57 1335.77    64.6 1331.53
    75.9 1329.36    98.7 1329.71   121.8 1326.88   132.8  1328.1   148.2 1333.85
   163.2 1317.43   170.7 1311.71   179.4 1300.13   184.2 1291.55     189 1287.67
   199.6 1289.38   243.1 1289.37  244.04 1288.47  245.28 1282.59  248.94 1278.73
  253.15 1271.26  287.19 1272.37   295.5 1277.93  321.27 1286.14   372.4 1290.42
   395.6 1296.28   417.7 1299.18     487 1297.86   596.6  1304.4   650.1 1305.17
#Mann= 6 ,-1 , 0
       0      .1       0   184.2    .016       0   243.1      .1       0
  248.94    .045       0   295.5      .1       0   417.7    .016       0
#XS Ineff= 2 ,-1
       0     185 1295.86     388 650.097  1295.5
Permanent Ineff=
       F       F
Bank Sta=248.94,295.5
XS Rating Curve= 0 ,0
Exp/Cntr(USF)=0,0
Exp/Cntr=0.5,0.3

Type RM Length L Ch R = 3 ,1733    ,,,
BEGIN DESCRIPTION:
State Route 20
Bridge Survey ID: 54089LIC020
Include 3 ft railing
END DESCRIPTION:
Bridge Culvert--1,0,-1,-1, 0
Deck Dist Width WeirC Skew NumUp NumDn MinLoCord MaxHiCord MaxSubmerge Is_Ogee
54,45,2.6,0, 13, 13, , , 0.98, 0, 0,0,,
       0     115     170     235     235     237     284     328     333     333
     345     380     500
1297.6291297.6291296.4851295.8621298.8621298.8621298.5081298.1811298.1811295.181
1295.222  1295.5  1295.5
                                1288.8621288.8621288.5081288.1811288.181
                        
       0     115     170     221     221     223     270     314     319     319
     345     380     500
1297.6291297.6291296.4851295.8621298.8621298.8621298.5081298.1811298.1811295.181
1295.222  1295.5  1295.5
                                1288.8621288.8621288.5081288.1811288.181
                        
BR Coef=-1 , 1 , 0 ,, 0 ,,,0.8,0,1.2,0,
WSPro=,,,, 1 ,,,, 0 ,,,, 0 ,,,,-1 ,-1 ,-1 , 0 , 0 , 0 , 0 , 0
BR U #Sta/Elev= 30
       0 1344.49    30.6 1343.05    49.4 1335.89      57 1335.77    64.6 1331.53
    75.9 1329.36    98.7 1329.71   121.8 1326.88   132.8  1328.1   148.2 1333.85
   163.2 1317.43   170.7 1311.71   179.4 1300.13   184.2 1291.55     189 1287.67
   199.6 1289.38   243.1 1289.37  244.04 1288.47  245.28 1282.59  248.94 1278.73
  253.15 1271.26  287.19 1272.37   295.5 1277.93  321.27 1286.14   372.4 1290.42
   395.6 1296.28   417.7 1299.18     487 1297.86   596.6  1304.4   650.1 1305.17
BR U #Mann= 6
       0      .1   184.2    .016   243.1      .1  248.94     .04   295.5      .1
   417.7    .016
BR D #Sta/Elev= 30
       0 1302.95    69.5 1297.39   116.2 1292.75   142.7 1291.51   159.1 1289.27
   206.1 1288.01  232.32 1283.69  245.28 1278.31  251.46 1273.45  262.84 1270.92
  271.92 1270.43   284.9  1271.1   290.6 1272.19  300.83 1277.09   316.6 1278.51
   332.5 1280.99   344.8 1281.55   387.1 1286.64   410.5 1288.68   410.5 1288.69
   459.5  1293.1   477.7 1294.21   505.2 1294.65   515.5 1292.97     521 1291.38
   524.9 1291.06   544.8 1291.68   562.3 1293.11   582.6 1292.95   650.1 1297.29
BR D #Mann= 5
       0      .1  245.28     .04  300.83      .1   410.5    .016   459.5      .1
BC Design=,, 0 ,, 0 ,,,,,,
BC Use User HTab Curves=0
BC User HTab FreeFlow(D)= 0

Type RM Length L Ch R = 1 ,1662    ,34.6,35.1,33.9
BEGIN DESCRIPTION:
Channel burned from 54089LIC018BD
END DESCRIPTION:
XS GIS Cut Line= 4
1999709.27471017283337.4814024291999612.96868295283503.656508223
1999491.82382063283672.3095114471999335.71628255283868.063408402
#Sta/Elev= 30
       0 1302.95    69.5 1297.39   116.2 1292.75   142.7 1291.51   159.1 1289.27
   206.1 1288.01  232.32 1283.69  245.28 1278.31  251.46 1273.45  262.84 1270.92
  271.92 1270.43   284.9  1271.1   290.6 1272.19  300.83 1277.09   316.6 1278.51
   332.5 1280.99   344.8 1281.55   387.1 1286.64   410.5 1288.68   410.5 1288.69
   459.5  1293.1   477.7 1294.21   505.2 1294.65   515.5 1292.97     521 1291.38
   524.9 1291.06   544.8 1291.68   562.3 1293.11   582.6 1292.95   650.1 1297.29
#Mann= 5 ,-1 , 0
       0      .1       0  245.28    .045       0  300.83      .1       0
   410.5    .016       0   459.5      .1       0
#XS Ineff= 2 ,-1
       0     211 1297.05     329 650.097  1295.5
Permanent Ineff=
       F       F
Bank Sta=245.28,300.83
XS Rating Curve= 0 ,0
Exp/Cntr(USF)=0,0
Exp/Cntr=0.8,0.6

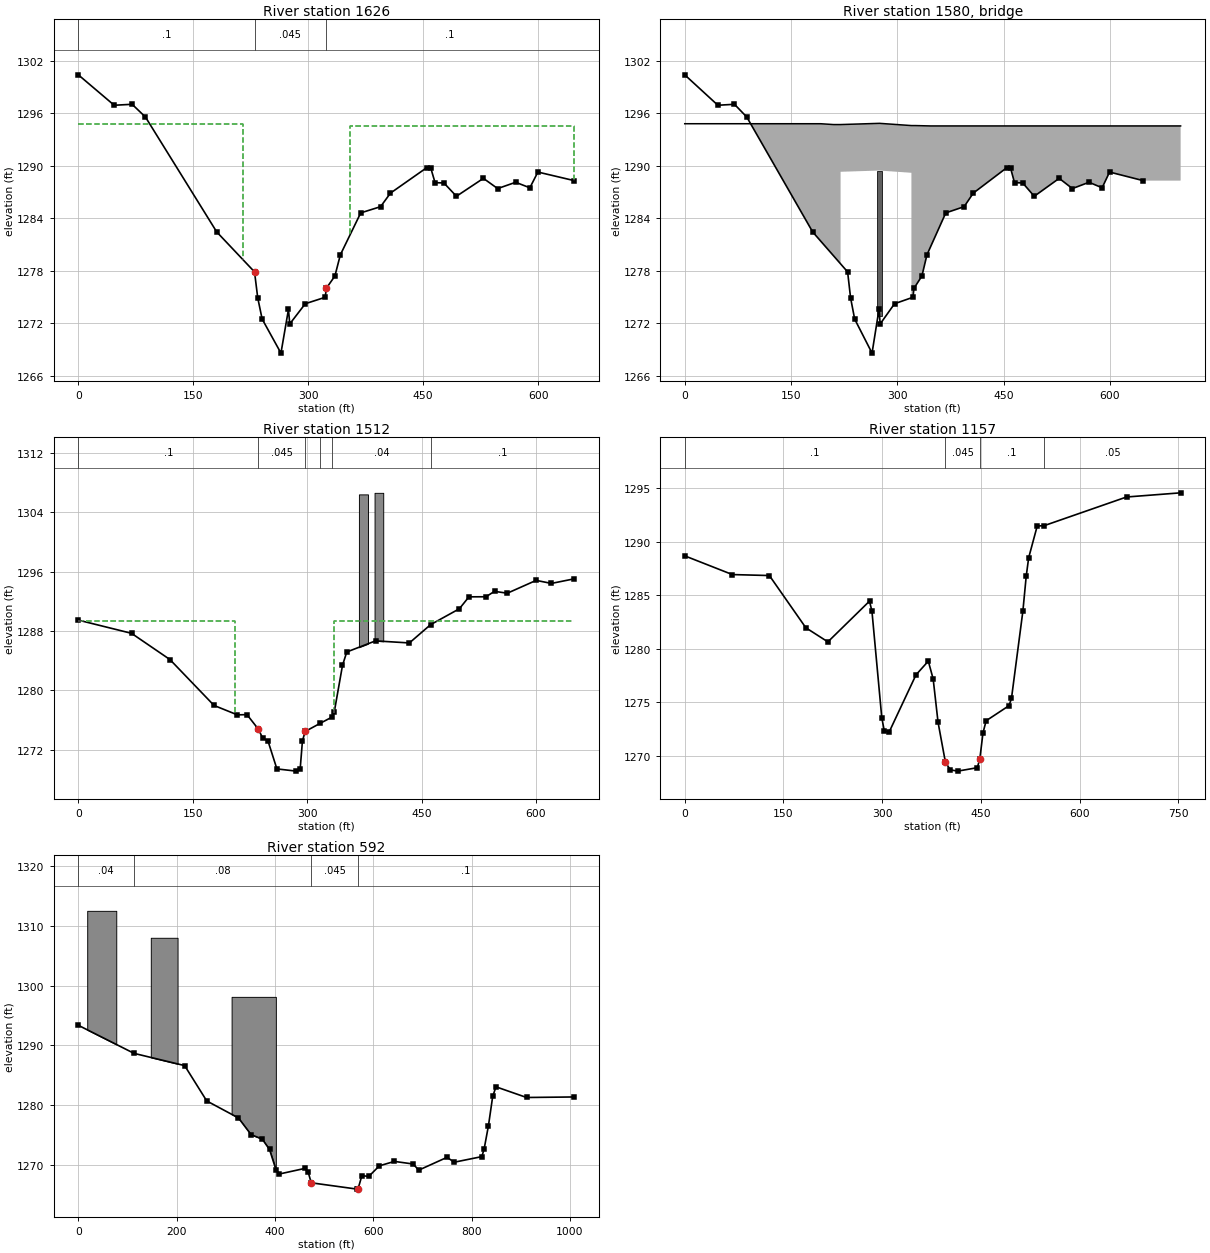
Type RM Length L Ch R = 1 ,1626    ,114.2,114.8,113.4
BEGIN DESCRIPTION:
Channel burned from 54089LIC012BU
END DESCRIPTION:
XS GIS Cut Line= 4
1999687.63399922283310.857332045  1999591.327972283477.032437839
1999470.18310967283645.6854410631999316.16355105283839.310306395
#Sta/Elev= 30
       0  1300.4    46.8 1296.92    70.2 1297.03    87.6 1295.57   180.6 1282.43
  229.92 1277.86  234.09  1274.9  239.85 1272.47   264.4 1268.57  274.19 1273.56
  275.91 1271.91  296.16 1274.22  322.23 1274.96   323.5 1275.97   334.8 1277.39
   341.9 1279.81   368.5 1284.61   394.4 1285.32   407.3 1286.87   454.8 1289.79
     460 1289.71   465.5 1288.07   477.1 1288.03   493.4 1286.51   528.6 1288.56
   547.2 1287.39   570.7 1288.11   589.2 1287.48   599.7 1289.28   647.1  1288.3
#Mann= 3 , 0 , 0
       0      .1       0  229.92    .045       0   323.5      .1       0
#XS Ineff= 2 , 0
       0     215 1294.81     355       0 1294.55
Permanent Ineff=
       F       F
Bank Sta=229.92,323.5
XS Rating Curve= 0 ,0
Exp/Cntr(USF)=0,0
Exp/Cntr=0.8,0.6

Type RM Length L Ch R = 3 ,1580    ,,,
BEGIN DESCRIPTION:
CSX
Bridge Survey ID:  54089LIC010
Railing is not included
END DESCRIPTION:
Bridge Culvert--1,0,-1,-1, 0
Deck Dist Width WeirC Skew NumUp NumDn MinLoCord MaxHiCord MaxSubmerge Is_Ogee
40,35,2.6,0, 11, 11, , , 0.98, 0, 0,0,,
       0     192     210     220     220     275     320     320     326     347
     700
1294.8071294.8071294.7121294.7121294.7121294.8521294.5961294.5961294.5961294.554
1294.554
                                1289.3121289.4521289.196
        
       0     192     210     220     220     275     320     320     326     347
     700
1294.8071294.8071294.7121294.7121294.7121294.8521294.5961294.5961294.5961294.554
1294.554
                                1289.3121289.4521289.196
        
Pier Skew, UpSta & Num, DnSta & Num=  ,275, 2 ,275, 2 , 0 , 0 , 0 ,,
       7       7
       0    1295
       7       7
       0    1295
BR Coef=-1 , 1 , 0 ,1.25, 0 ,,,0.8,0,2,0,
WSPro=,,,, 1 ,,,, 0 ,,,, 0 ,,,,-1 ,-1 ,-1 , 0 , 0 , 0 , 0 , 0
BR U #Sta/Elev= 30
       0  1300.4    46.8 1296.92    70.2 1297.03    87.6 1295.57   180.6 1282.43
  229.92 1277.86  234.09  1274.9  239.85 1272.47   264.4 1268.57  274.19 1273.56
  275.91 1271.91  296.16 1274.22  322.23 1274.96   323.5 1275.97   334.8 1277.39
   341.9 1279.81   368.5 1284.61   394.4 1285.32   407.3 1286.87   454.8 1289.79
     460 1289.71   465.5 1288.07   477.1 1288.03   493.4 1286.51   528.6 1288.56
   547.2 1287.39   570.7 1288.11   589.2 1287.48   599.7 1289.28   647.1  1288.3
BR U #Mann= 3
       0      .1  229.92     .04   323.5      .1
BR D #Sta/Elev= 30
       0 1289.47    69.7 1287.69   120.1 1284.15   177.9 1277.96   208.5 1276.69
   221.1 1276.72   236.1 1274.75   241.7 1273.54   248.5 1273.21   260.3  1269.4
   285.7  1269.1   290.8 1269.35   293.8 1273.18   297.4 1274.45   316.7 1275.53
   333.1 1276.42   335.5 1277.06   346.3 1283.36   351.9 1285.17   389.6 1286.67
     434 1286.39   461.7 1288.85   499.5    1291   512.1 1292.61   534.4 1292.62
   545.6 1293.35   562.4  1293.1   600.2 1294.83   620.2 1294.42   650.1 1295.04
BR D #Mann= 6
       0      .1   236.1     .04   297.4      .1   316.7    .016   333.1     .04
   461.7      .1
BC Design=,, 0 ,, 0 ,,,,,,
BC Use User HTab Curves=0
BC User HTab FreeFlow(D)= 0

Type RM Length L Ch R = 1 ,1512    ,334.3,354.5,367.9
XS GIS Cut Line= 4
1999610.40616564283228.5911009521999514.10013842283394.766206746
 1999392.9552761 283563.419209971999236.84773802283759.173106925
#Sta/Elev= 30
       0 1289.47    69.7 1287.69   120.1 1284.15   177.9 1277.96   208.5 1276.69
   221.1 1276.72   236.1 1274.75   241.7 1273.54   248.5 1273.21   260.3  1269.4
   285.7  1269.1   290.8 1269.35   293.8 1273.18   297.4 1274.45   316.7 1275.53
   333.1 1276.42   335.5 1277.06   346.3 1283.36   351.9 1285.17   389.6 1286.67
     434 1286.39   461.7 1288.85   499.5    1291   512.1 1292.61   534.4 1292.62
   545.6 1293.35   562.4  1293.1   600.2 1294.83   620.2 1294.42   650.1 1295.04
#Mann= 6 ,-1 , 0
       0      .1       0   236.1    .045       0   297.4      .1       0
   316.7    .016       0   333.1     .04       0   461.7      .1       0
#XS Ineff= 2 ,-1
       0     205  1289.3     335 650.097  1289.3
Permanent Ineff=
       F       F
#Block Obstruct= 2 ,-1
  367.84  379.69 1306.43  388.33  399.72 1306.64
Bank Sta=236.1,297.4
XS Rating Curve= 0 ,0
Exp/Cntr(USF)=0,0
Exp/Cntr=0.5,0.3

Type RM Length L Ch R = 1 ,1157    ,542.1,564.8,560.2
XS GIS Cut Line= 2
 1999617.8717926282990.1939282711998953.41026289283345.520949509
#Sta/Elev= 30
       0 1288.69    72.4 1286.94   128.6 1286.85     184 1281.97   217.5 1280.65
   280.8 1284.46   284.5 1283.49   299.4 1273.57   303.1 1272.36   310.5 1272.21
   351.4 1277.57   370.1 1278.85   377.5 1277.18   384.9 1273.14   396.1  1269.4
   403.5 1268.69   414.7 1268.57   444.5 1268.89   448.4 1269.71   453.2 1272.15
     458 1273.28   492.8 1274.69   496.5 1275.38   513.8 1283.52   518.9  1286.8
   522.6 1288.51   535.6 1291.48   546.1 1291.51   671.3 1294.19   753.5 1294.58
#Mann= 4 ,-1 , 0
       0      .1       0   396.1    .045       0   448.4      .1       0
   546.1     .05       0
Bank Sta=396.1,448.4
XS Rating Curve= 0 ,0
Exp/Cntr(USF)=0,0
Exp/Cntr=0.3,0.1

Type RM Length L Ch R = 1 ,592     ,,,
XS GIS Cut Line= 3
1999749.34279046282652.6332580951999187.92609691282641.973447458
1998768.64021185282798.317336803
#Sta/Elev= 30
       0 1293.36   113.4 1288.65   216.3  1286.6   261.3 1280.67   325.8 1277.82
   351.5 1275.02   374.1 1274.28     389 1272.53   402.1 1269.15   408.7 1268.41
   461.2 1269.36   467.7 1268.72   473.9 1266.94   567.4 1265.88   569.3 1265.96
   576.9 1268.13     591 1268.02   612.6 1269.79   643.2 1270.53   681.5 1270.09
   692.5 1269.06   750.4 1271.22   764.6 1270.39   820.9 1271.33   825.6 1272.57
   834.5 1276.53   843.1 1281.42   849.8 1283.04   912.1 1281.25    1009 1281.34
#Mann= 4 ,-1 , 0
       0     .04       0   113.4     .08       0   473.9    .045       0
   569.3      .1       0
#Block Obstruct= 3 ,-1
   18.05   77.18 1312.56  147.42   201.9 1308.04  311.84   401.9 1298.13
Bank Sta=473.9,569.3
XS Rating Curve= 0 ,0
Exp/Cntr(USF)=0,0
Exp/Cntr=0.3,0.1
LCMann Table=0

Chan Stop Cuts=-1
Use User Specified Reach Order=0
Composite Channel Slope=5